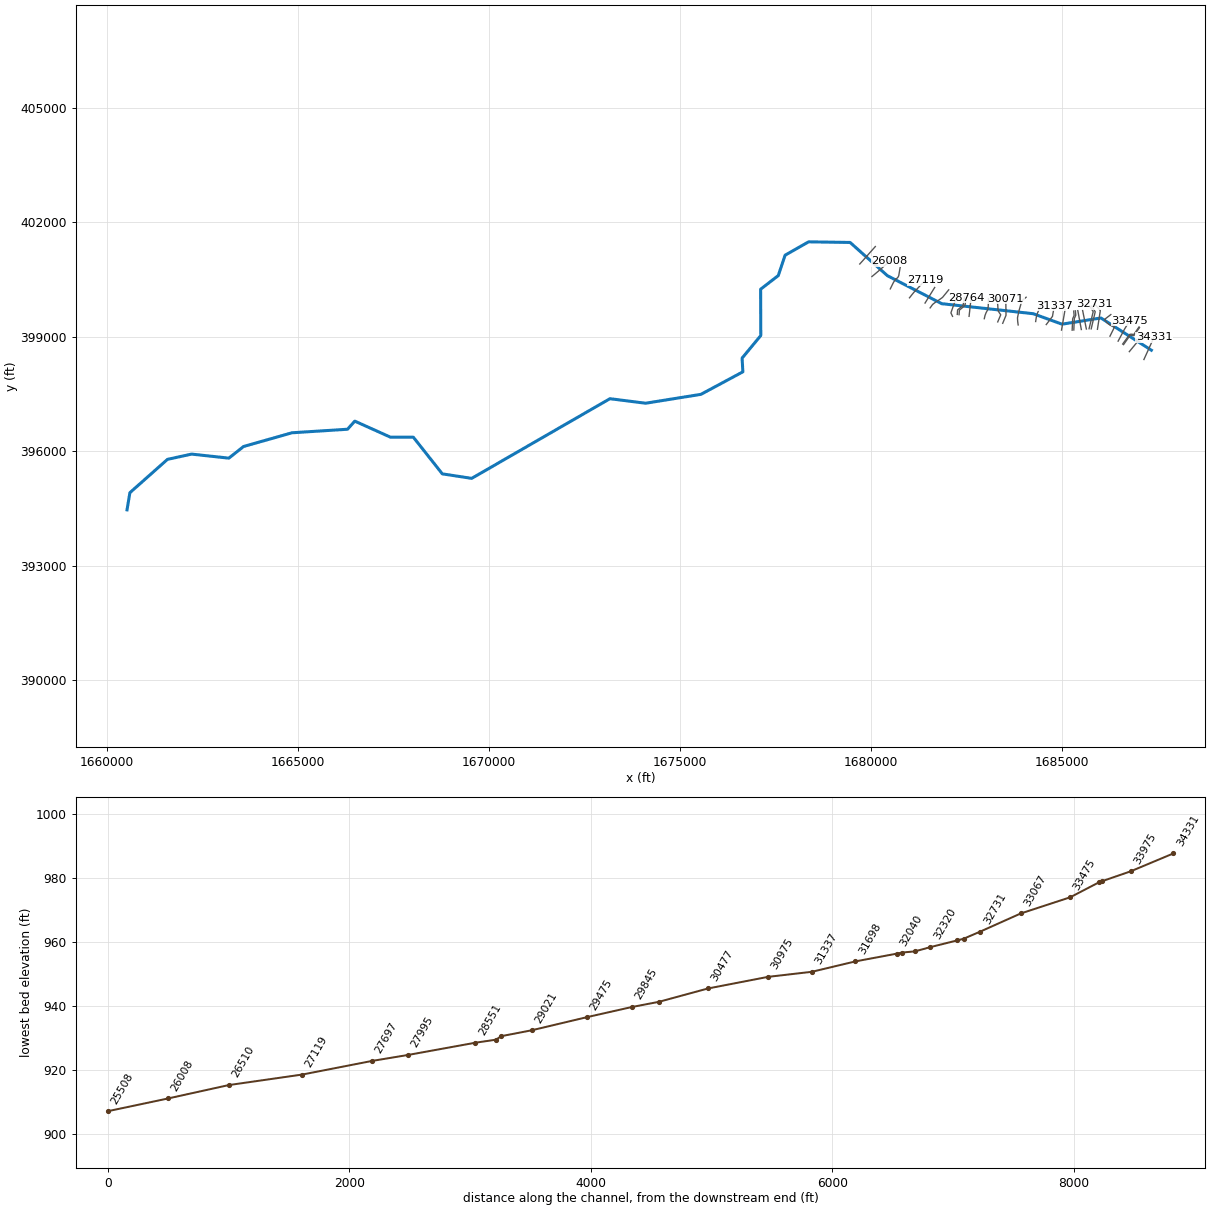
--- WILLEYFK.prj (project) ---

Proj Title=WILLEYFK
Current Plan=p01
Default Exp/Contr=0,0
English Units
Geom File=g01
Flow File=f01
Plan File=p01
BEGIN DESCRIPTION:
---------- MODELED AS PART OF WVEMD CTP PROGRAM, 2023----------
Stream Name: Willey Fork
Flood Zone:  AFH
Wetzel County, WV
HEC-RAS Version: RAS 6.3
Vertical Datum: NAVD88
Projection: NAD 1983 StatePlane West Virginia S FIPS 4702 (US Feet)
Terrain: 1-meter West Virginia FEMA R3 South Central (collected 2018-2020)
Land Use: 2019 NLCD
Hydrologic Method:
WV 2010 Regional Regression Equations
Additional Model Notes:
None
END DESCRIPTION:
DSS Export Rating Curves= 0
DSS Export Rating Curve Sorted= 0
DSS Export Volume Flow Curves= 0
DXF OffsetX= 0
DXF OffsetY= 0
DXF ScaleX= 0
DXF ScaleY= 0

--- WILLEYFK.p01 (plan) ---

Plan Title=Floodplain
Program Version=6.30
Short Identifier=Floodplain
Geom File=g01
Flow File=f01
Subcritical Flow
K Sum by GR= 0
Std Step Tol= 0.01
Critical Tol= 0.01
Num of Std Step Trials= 20
Max Error Tol= 0.3
Flow Tol Ratio= 0.001
Split Flow NTrial= 30
Split Flow Tol= 0.02
Split Flow Ratio= 0.02
Log Output Level= 0
Friction Slope Method= 1
Unsteady Friction Slope Method= 2
Unsteady Bridges Friction Slope Method= 1
Parabolic Critical Depth
Global Vel Dist= 0 , 0 , 0
Global Log Level= 0
CheckData=True
Encroach Param=-1 ,0,0, 0
Mapping Interval=1HOUR
Computation Time Step Use Courant=        0
Computation Time Step Use Time Series=    0
Computation Time Step Count To Double=0
Computation Time Step Max Doubling=0
Computation Time Step Max Halving=0
Computation Time Step Residence Courant=0
Run HTab= 0
Run UNet= 0
Run Sediment= 0
Run PostProcess= 0
Run WQNet= 0
Run RASMapper= 0
UNET Theta= 0
UNET Theta Warmup= 0
UNET ZTol= 0
UNET ZSATol= 0
UNET MxIter= 0
UNET Max Iter WO Improvement= 0
UNET MaxInSteps= 0
UNET DtIC= 0
UNET DtMin= 0
UNET MaxCRTS= 0
UNET WFStab= 0
UNET SFStab= 0
UNET WFX= 1
UNET SFX= 1
UNET Gravity=32.17405
UNET 1D Methodology=Finite Difference
UNET DSS MLevel= 1
UNET Pardiso=0
UNET DZMax Abort= 0
UNET Use Existing IB Tables= 0
UNET Froude Reduction=False
UNET Froude Limit= 0
UNET Froude Power= 0
UNET D1 Cores= 0
UNET WindReference=Eulerian
UNET WindDragFormulation=Hsu (1988)
UNET D2 Coriolis=0
UNET D2 Cores= 0
UNET D2 Theta= 1
UNET D2 Theta Warmup= 1
UNET D2 Z Tol= 0.01
UNET D2 Volume Tol= 0.01
UNET D2 Max Iterations= 20
UNET D2 Equation= 0
UNET D2 RampUpFraction=0.1
UNET D2 TimeSlices= 1
UNET D2 Turbulence Formulation=Non-Conservative (original)
UNET D2 Eddy Viscosity=0.3
UNET D2 Transverse Eddy Viscosity=0.1
UNET D2 Smagorinsky Mixing=0
UNET D2 BCVolumeCheck=0
UNET D2 Cores=0
UNET D2 SolverType=PARDISO (Direct)
UNET D2 Minimum Iterations= 3
UNET D2 Maximum Iterations= 30
UNET D2 Restart Number= 10
UNET D2 Relaxation Coeff=1.3
UNET D2 SOR Precondition Iterations= 10
UNET D2 ILUT Maximum Fill= 8
UNET D2 ILUT Tolerance=1E-08
UNET D2 Convergence Tolerance=0.00001
UNET D1D2 MaxIter= 0
UNET D1D2 ZTol=0.01
UNET D1D2 QTol=0.1
UNET D1D2 MinQTol=1
Write IC File= 0
Write IC File at Fixed DateTime=0
Write IC File at Sim End=0
Echo Input=False
Echo Parameters=False
Echo Output=False
Write Detailed= 0
HDF Write Warmup=0
HDF Write Time Slices=0
HDF Flush=0
HDF Compression= 1
HDF Chunk Size= 1
HDF Spatial Parts= 1
HDF Use Max Rows=0
HDF Fixed Rows= 1
Calibration Method= 0
Calibration Iterations= 20
Calibration Max Change=0.05
Calibration Tolerance=0.2
Calibration Maximum=1.5
Calibration Minimum=0.5
Calibration Optimization Method= 1
WQ AD Non Conservative
WQ ULTIMATE=-1
WQ Max Comp Step=1HOUR
WQ Output Interval=15MIN
WQ Output Selected Increments= 0
WQ Output face flow=0
WQ Output face velocity=0
WQ Output face area=0
WQ Output face dispersion=0
WQ Output cell volume=0
WQ Output cell surface area=0
WQ Output cell continuity=0
WQ Output cumulative cell continuity=0
WQ Output face conc=0
WQ Output face dconc_dx=0
WQ Output face courant=0
WQ Output face peclet=0
WQ Output face adv mass=0
WQ Output face disp mass=0
WQ Output cell mass=0
WQ Output cell source sink temp=0
WQ Output nsm pathways=0
WQ Output nsm derived pathways=0
WQ Create Restart=0
WQ Fixed Restart=0
WQ System Summary=0
WQ Write To DSS=0
Sorting and Armoring Iterations= 10
XS Update Threshold= 0.02
Bed Roughness Predictor= 0
Hydraulics Update Threshold= 0.02
Energy Slope Method= 1
Volume Change Method= 1
Sediment Retention Method= 0
Sediment TS Multiplier= 1
Warm Up Method= 0
XS Weighting Method= 0
Number of US Weighted Cross Sections= 1
Number of DS Weighted Cross Sections= 1
Upstream XS Weight=0
Main XS Weight=1
Downstream XS Weight=0
Number of DS XS's Weighted with US Boundary= 1
Upstream Boundary Weight= 1
Weight of XSs Associated with US Boundary= 0
Number of US XS's Weighted with DS Boundary= 1
Downstream Boundary Weight= 0.5
Weight of XSs Associated with DS Boundary= 0.5
Percentile Method= 0
Sediment Output Level= 3
Mass or Volume Output= 0
Output Increment Type= 1
Profile and TS Output Increment= 1
Transport Output Increment 1
XS Output Flag= 0
XS Output Increment= 10
Read HDF5 Sediment Hotstart= 0
Sediment Hotstart Type= 0
Write Gradation File= 0
Read Gradation Hotstart= 0
Write HDF5 File= 1
Write Binary Output= 1
Write DSS Sediment File= 0
DSS Sediment Output Type= 1
SV Curve= 0
Specific Gage Flag= 0
Subcell Erosion Methods= 0
Subcell Deposition Methods= 0
Advection Scheme= 1
Matrix Solver= 0
Implicit Weighting Factor= 1
Maximum Outer Loop Convergence Iterations= 5
Convergence Maximum Absolute= 0.001
Convergence RMSE= 0.0001
Grain Fractions Max Abs Error= 0.001
Max Subgrid Regions= 1
Max Subgrid Length Scale= 3.402823E+38
Initial Layer Thickness= 3.402823E+38
Min Layer Thickness= 3.402823E+38
Max Layer Thickness= 3.402823E+38
Number of Layers= 5

--- WILLEYFK.f01 (steady flow) ---

Flow Title=Flow
Program Version=4.00
Number of Profiles=1
Profile Names=F01pct
River Rch & RM=WILLEYFK,Main,34331
    1060
River Rch & RM=WILLEYFK,Main,30071
    1180
River Rch & RM=WILLEYFK,Main,29845
    1370
River Rch & RM=WILLEYFK,Main,25007
    1640
River Rch & RM=WILLEYFK,Main,22983
    1830
River Rch & RM=WILLEYFK,Main,18008
    2210
River Rch & RM=WILLEYFK,Main,16514
    2460
River Rch & RM=WILLEYFK,Main,7972
    2830
River Rch & RM=WILLEYFK,Main,5030
    3530
Boundary for River Rch & Prof#=WILLEYFK,Main      ,1
Up Type=0
Dn Type=3
Dn Slope=0.003727

--- WILLEYFK.g01 (geometry) ---

Geom Title=Geometry
Program Version=6.30

River Reach=WILLEYFK        ,Main
Reach XY= 30
1687339.07784437398650.047316101     1686017.976      399493.871
     1684999.742      399331.268     1684245.021      399605.759
     1681852.309      399868.188     1680430.332      400600.635
     1679451.982      401472.417     1678366.632      401488.414
     1677750.894      401138.933     1677572.222      400604.607
     1677109.838      400246.589     1677114.228      399033.378
     1676625.161       398442.31     1676644.413      398082.602
1675547.35339217397492.7205910461674097.53636051397260.055342853
     1673165.769      397379.386      1669546.35      395291.692
     1668776.596      395409.9331668018.83011913396369.866969554
     1667418.882      396371.206     1666485.271       396791.34
     1666295.357      396578.817     1664839.939      396486.023
     1663573.858      396126.358     1663188.034      395821.631
     1662212.261      395927.322     1661581.457      395789.376
     1660597.543      394916.357     1660522.437      394466.404

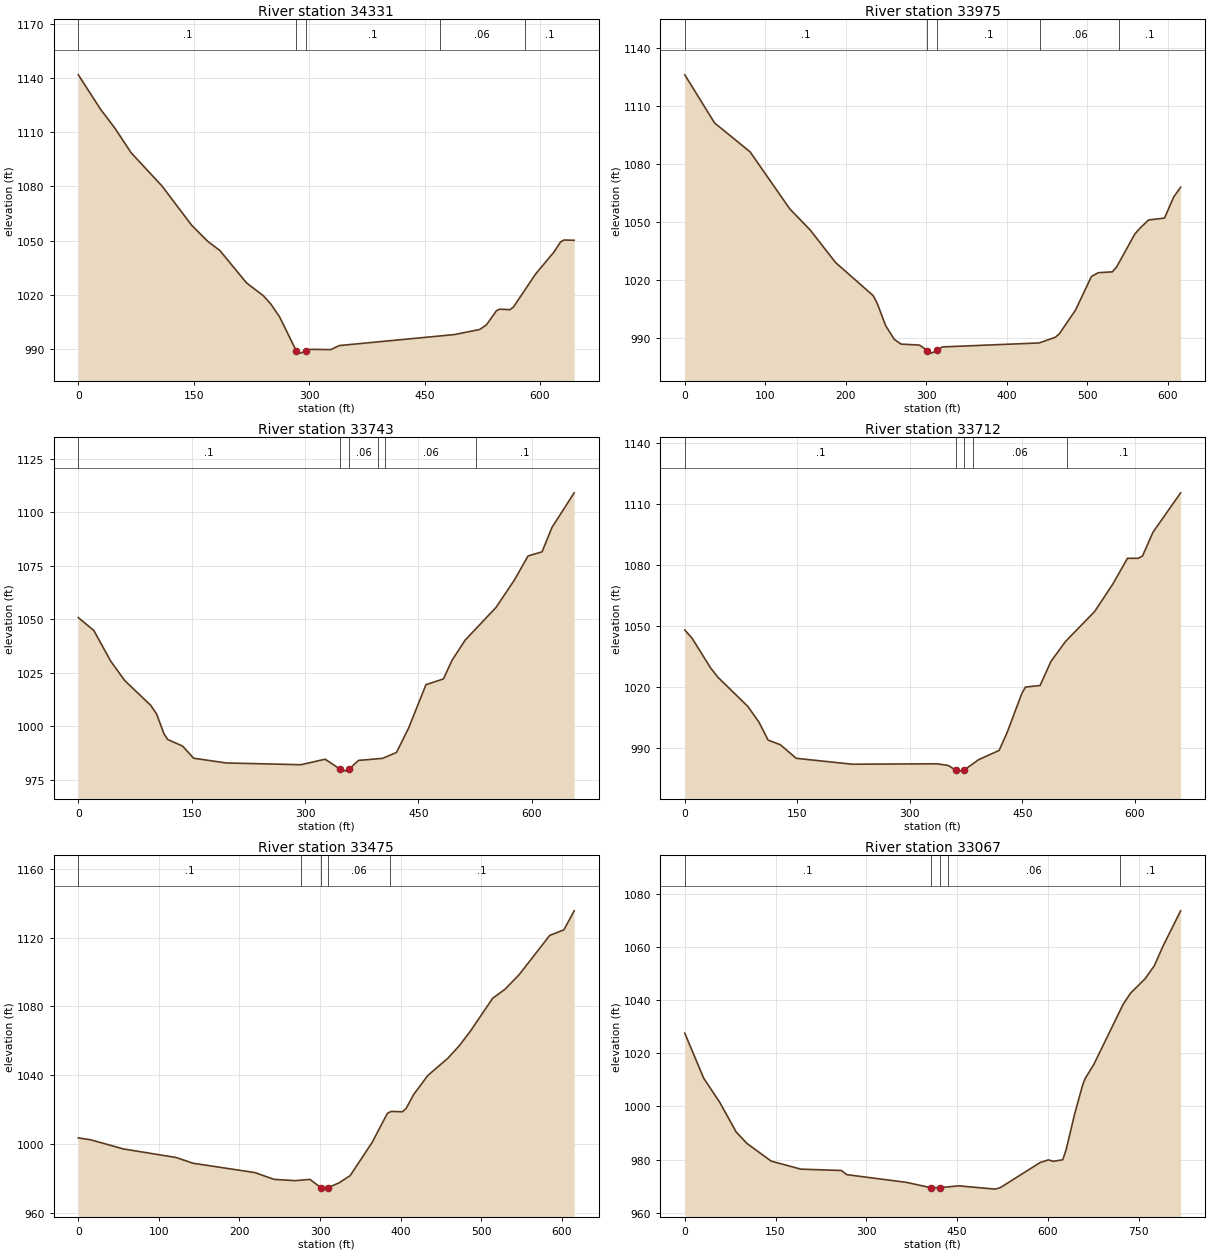
Type RM Length L Ch R = 1 ,34331   ,356.8,355.3,353.6
XS GIS Cut Line= 2
1687144.23032504398405.4412127151687410.06545375398992.561742392
#Sta/Elev= 30
       0 1141.87    28.8 1122.84    47.3 1112.44    68.7 1098.65   108.8 1080.23
   147.3 1058.51   168.5 1049.49     184  1044.5   218.6 1026.56   240.5 1019.43
   250.1 1014.89   261.6 1007.72   283.3  988.88   288.8  987.62   295.4   988.8
     302  989.71   328.3  989.58   339.1  991.81   488.9  997.91   521.5 1000.69
   530.3 1003.19   543.5 1011.15   547.9 1011.99     561 1011.69   565.4 1013.08
   594.6 1031.59   618.1 1043.57   626.9 1049.28   631.3 1050.31   644.5 1050.17
#Mann= 5 ,-1,0
       0      .1       0   283.3    .045       0   295.4      .1       0
     470     .06       0     580      .1       0
Bank Sta=283.3,295.4
XS Rating Curve= 0 ,0
Exp/Cntr(USF)=0,0
Exp/Cntr=0.3,0.1

Type RM Length L Ch R = 1 ,33975   ,238.1,232.5,227.4
BEGIN DESCRIPTION:
Structure XS 4
END DESCRIPTION:
XS GIS Cut Line= 6
1686762.51348184398612.0091764181686925.41473085398809.815211251
1686988.98645408398887.0073140861687036.00046767398945.449126333
  1687088.143408399015.8600747591687154.90935059399085.957047418
#Sta/Elev= 30
       0 1126.33      37 1101.37    81.1 1086.38   130.2  1056.9   156.1 1045.68
   187.2 1028.99   233.9 1011.83     239 1007.78   249.4  996.28   260.1  989.15
   268.6  986.67   291.4  986.18   301.2  983.35   306.4     982  313.39983.4276
   319.8  985.22   440.1  987.28     460  990.21     465  991.96   485.2 1004.32
     505 1021.79   513.6 1023.72   530.9 1024.15   536.4 1026.84   558.9 1043.81
   565.2 1046.78   575.9 1051.06   595.7 1052.04     607 1062.89   615.7 1068.04
#Mann= 5 ,-1,0
       0      .1       0   301.2    .045       0  313.39      .1       0
  441.25     .06       0  538.87      .1       0
Bank Sta=301.2,313.39
XS Rating Curve= 0 ,0
Exp/Cntr(USF)=0,0
Exp/Cntr=0.3,0.1

Type RM Length L Ch R = 1 ,33743   ,29.8,30.6,30.4
BEGIN DESCRIPTION:
Structure XS 3
END DESCRIPTION:
XS GIS Cut Line= 6
1686611.39505665398795.7795308311686782.41726219399038.598794358
1686813.07218582399040.2122113921686859.05457128399037.792085841
1686879.22228419399028.1115836411687028.46335978 399241.08263205
#Sta/Elev= 30
       0 1050.79    20.5 1044.79    42.9 1030.42    61.3  1021.4    95.8 1009.76
   103.7 1005.63   113.5  996.32   118.3  993.74   137.9  990.72   152.6     985
   195.8  982.79   294.5  981.97   326.7  984.55  346.51979.8835   354.8  978.97
   358.2979.8884   370.8  983.98   402.8  984.95   421.1  987.72   437.3  999.27
   460.1 1019.43   483.2 1022.12   494.7  1030.9   511.9 1040.26   552.9 1055.61
   577.4 1068.56   595.2 1079.65   613.7 1081.58   626.8 1092.97   656.2 1109.19
#Mann= 6 ,-1,0
       0      .1       0  346.51    .045       0   358.2     .06       0
  396.12      .1       0  406.12     .06       0  526.12      .1       0
Bank Sta=346.51,358.2
XS Rating Curve= 0 ,0
Exp/Cntr(USF)=0,0
Exp/Cntr=0.3,0.1

Type RM Length L Ch R = 1 ,33712   ,231.6,237,241.7
BEGIN DESCRIPTION:
Structure XS 2
END DESCRIPTION:
XS GIS Cut Line= 6
1686588.80721818398812.7204096821686773.54346851399064.413466893
1686805.00510066399068.4470094761686847.76065204399066.026883926
1686879.22228419399059.5732157921687016.36273203399258.830219418
#Sta/Elev= 30
       0 1048.02     9.7 1043.99    34.5  1029.3    44.4 1024.69    84.1 1010.38
      99 1002.57     111  993.84   127.3  991.54   148.6  984.85   223.1  981.94
   336.1  982.15   351.1  981.33  361.59978.9011   367.1  978.54   371.5978.8894
   391.7   984.2   418.9  988.73   429.8  997.76   449.2 1016.84     454 1019.94
   473.5 1020.71     488 1032.58   507.4  1042.4   546.3 1057.19   570.6 1070.76
   589.9 1083.34   604.3 1083.37     610 1084.49     624 1096.23   660.8  1115.6
#Mann= 5 ,-1,0
       0      .1       0  361.59    .045       0   371.5      .1       0
  383.93     .06       0  508.87      .1       0
Bank Sta=361.59,371.5
XS Rating Curve= 0 ,0
Exp/Cntr(USF)=0,0
Exp/Cntr=0.3,0.1

Type RM Length L Ch R = 1 ,33475   ,398.3,408.7,414.3
BEGIN DESCRIPTION:
Structure XS 1
END DESCRIPTION:
XS GIS Cut Line= 6
1686469.28900267398886.9187315851686554.58312343399046.845249012
1686636.93532093399201.2576698361686675.97133209399265.645336345
1686723.03127734399340.299714595 1686771.5357735399422.556439832
#Sta/Elev= 30
       0 1003.66    15.1 1002.57    56.2  997.21   121.5  992.26   142.2  988.94
   219.1   983.5   242.8  979.57   269.3  978.81   287.4  979.55     301  974.75
   305.6  973.89   310.1  974.79   323.7  977.57   337.4  981.77   364.8  1001.2
   383.5 1017.92   388.2 1019.03   402.2 1018.84   406.9 1020.86   416.2  1028.9
   433.7 1039.91   458.6 1049.96   472.8 1057.22     486 1065.33   514.3 1084.82
   529.4 1089.98   547.1  1098.5     585  1121.3   602.6 1124.54   615.3 1135.57
#Mann= 5 ,-1,0
       0      .1       0  276.25     .06       0     301    .045       0
   310.1     .06       0  386.25      .1       0
Bank Sta=301,310.1
XS Rating Curve= 0 ,0
Exp/Cntr(USF)=0,0
Exp/Cntr=0.3,0.1

Type RM Length L Ch R = 1 ,33067   ,342.6,335.5,334.5
BEGIN DESCRIPTION:
Low water crossing
END DESCRIPTION:
XS GIS Cut Line= 6
1686255.74261167399016.4952671821686376.21697022399260.044150284
 1686260.9429437399305.1136944881686181.20451934399364.050790754
1686111.86675902399455.0566011661686278.83289765399583.026670433
#Sta/Elev= 30
       0 1027.61    31.3 1010.63    58.1 1001.45    84.8  990.41   102.7  986.06
   142.9  979.38   191.9  976.37   258.9  975.86   267.8  974.29   366.3  971.39
   406.5  969.38  421.84969.4064   452.9  970.08   512.9  968.84   521.5   969.4
   587.1  978.85   600.9  979.86   609.1  979.31   624.6  979.92   630.3  983.79
   644.6  997.47   657.5 1008.08   661.6 1010.52   675.9 1015.81   724.4  1038.5
   736.4 1042.64   760.6 1048.12   775.8 1052.99     790 1060.28   819.4 1073.74
#Mann= 5 ,-1,0
       0      .1       0   406.5    .045       0  421.84      .1       0
  435.49     .06       0  719.05      .1       0
Bank Sta=406.5,421.84
XS Rating Curve= 0 ,0
Exp/Cntr(USF)=0,0
Exp/Cntr=0.3,0.1

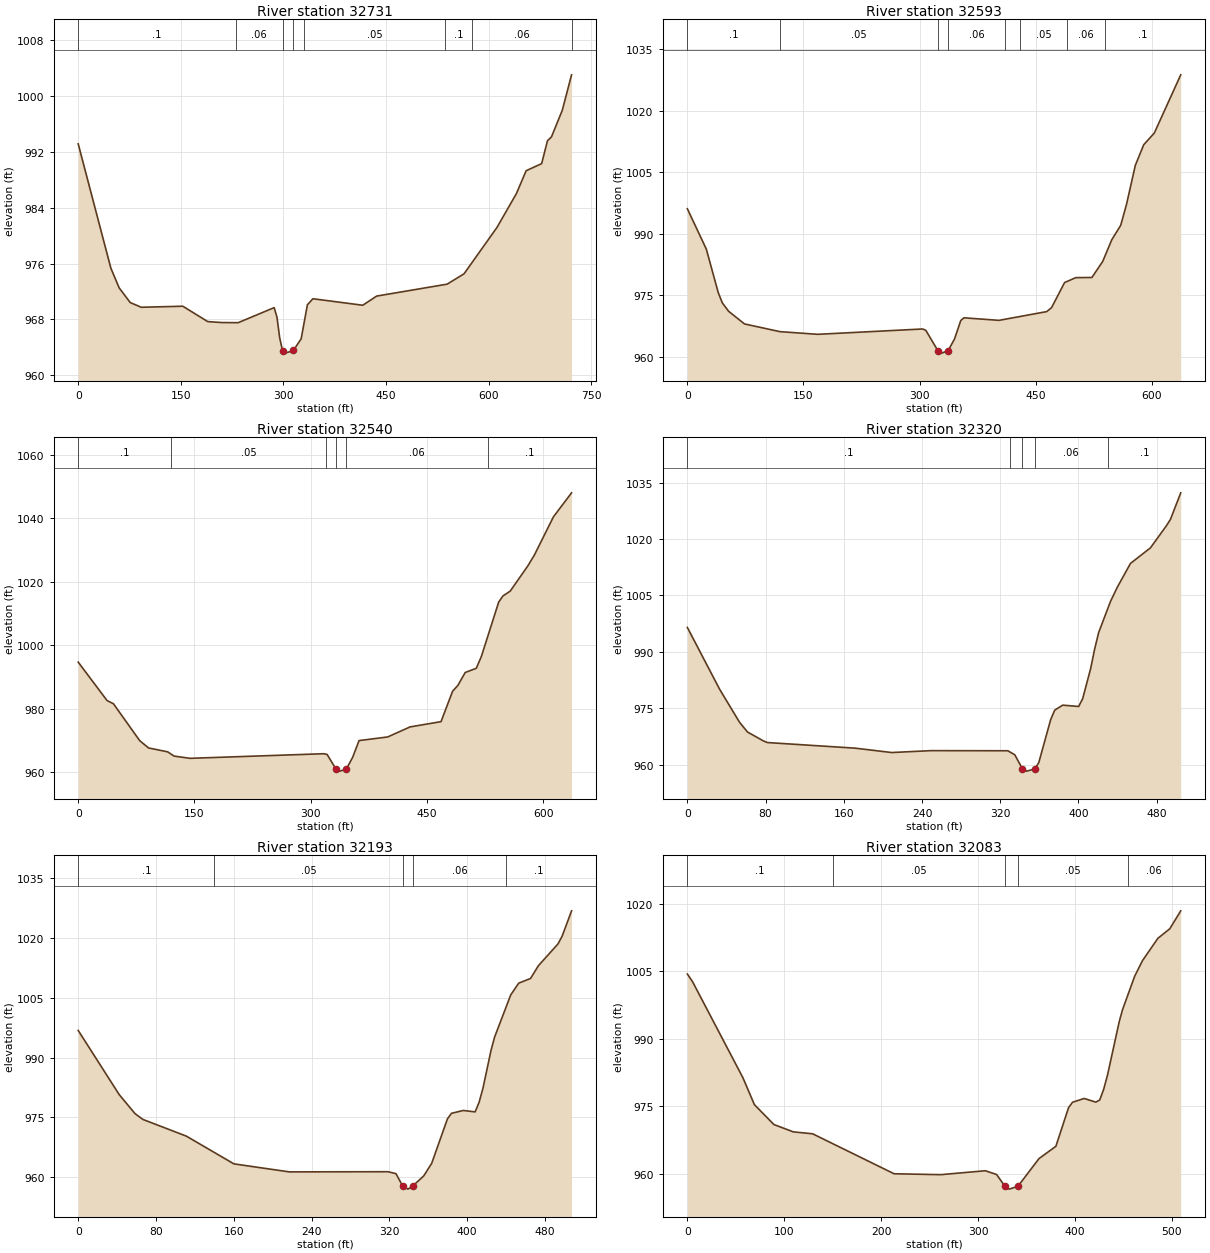
Type RM Length L Ch R = 1 ,32731   ,138.1,137.8,136.9
BEGIN DESCRIPTION:
Structure XS 4
END DESCRIPTION:
XS GIS Cut Line= 3
1685927.65359421399197.412183573 1686002.9463891399687.711693168
 1685856.8425133399858.913167268
#Sta/Elev= 30
       0  993.15    47.7  975.35    59.8  972.53      76  970.42    92.2  969.74
   152.9  969.89   189.3  967.69   209.6  967.55   233.8  967.53   286.4  969.69
   290.5  968.33   294.5  965.35   298.6  963.54   302.6  963.17   314.6963.5558
   325.9  965.23     335   970.1   343.1  970.96   415.9  970.03   436.2  971.34
   539.2  973.05   563.9  974.53   612.1  981.18   640.5  986.03   654.7   989.3
   677.4  990.32   685.9   993.6   691.7  994.14   707.5  997.95   721.1 1003.04
#Mann= 8 ,-1,0
       0      .1       0     230     .06       0   298.6    .045       0
   314.6     .06       0     330     .05       0  536.05      .1       0
  576.05     .06       0  721.12      .1       0
Bank Sta=298.6,314.6
XS Rating Curve= 0 ,0
Exp/Cntr(USF)=0,0
Exp/Cntr=0.3,0.1

Type RM Length L Ch R = 1 ,32593   ,53,53.1,52.9
BEGIN DESCRIPTION:
Structure XS 3
END DESCRIPTION:
XS GIS Cut Line= 3
1685764.14183976 399208.67372804 1685869.8235351399656.353131918
1685774.41644903399806.068866986
#Sta/Elev= 30
       0  996.08    24.5  986.25    39.8  975.72    45.1  973.19    53.3  971.12
    73.8  968.04   119.6  966.16   168.4  965.51     304  966.81   308.1  966.49
  323.72961.5123   328.7  960.93   336.9  961.52   345.1  964.34   353.3  968.88
   357.4  969.53   402.6  968.91   464.3  971.04   470.6  972.01   487.4  978.12
   501.9  979.31   522.7  979.35   536.7  983.27   548.3  988.51   559.9  992.04
   567.4  997.14   578.8 1006.65   589.7 1011.69   603.3 1014.51   637.5  1028.7
#Mann= 8 ,-1,0
       0      .1       0     120     .05       0  323.72    .045       0
   336.9     .06       0     410     .07       0     430     .05       0
  489.98     .06       0  539.98      .1       0
Bank Sta=323.72,336.9
XS Rating Curve= 0 ,0
Exp/Cntr(USF)=0,0
Exp/Cntr=0.3,0.1

Type RM Length L Ch R = 1 ,32540   ,219,220.8,224.5
BEGIN DESCRIPTION:
Structure XS 2
END DESCRIPTION:
XS GIS Cut Line= 3
1685708.36538944 399212.343231351685816.98268743399658.554833904
1685721.57560136399808.270568972
#Sta/Elev= 30
       0  994.73    37.3  982.62    45.5  981.62    79.4     970    90.8  967.71
   115.5  966.48   123.7  965.15   144.3  964.44   317.2  965.89   321.3  965.65
  332.77  961.04   337.7  960.41     346  961.02   354.2  964.74   362.5  970.03
   399.5  971.17   428.3  974.33   468.3  975.99   483.2  985.55   490.1  987.42
   499.5  991.47   513.8  992.79   520.4  996.54   542.7 1013.62   548.2 1015.57
   557.6 1017.09   580.2 1024.98   588.8 1028.45   613.4 1040.49   636.8 1048.04
#Mann= 6 ,-1,0
       0      .1       0     120     .05       0     320     .06       0
  332.77    .045       0     346     .06       0  529.24      .1       0
Bank Sta=332.77,346
XS Rating Curve= 0 ,0
Exp/Cntr(USF)=0,0
Exp/Cntr=0.3,0.1

Type RM Length L Ch R = 1 ,32320   ,127,126.9,126.7
BEGIN DESCRIPTION:
Structure XS 1
END DESCRIPTION:
XS GIS Cut Line= 2
1685637.91092588399204.2703240671685538.10043584 399698.91937032
#Sta/Elev= 30
       0  996.49    32.9  980.12    53.3  971.33    61.5  968.72    77.8  966.35
    81.9  965.92   171.7  964.43   208.9  963.27   249.2  963.77   327.7  963.74
   334.9  962.67  342.63958.9542   347.1  958.33   355.3   958.9   359.4  960.59
   371.6  972.04   375.7  974.53   383.9  975.86   400.2   975.5   404.3  977.58
   412.4  985.52   416.5  990.69   420.6  995.11   432.8 1003.44   439.8 1007.22
   453.2 1013.51   473.6 1017.64   489.9  1023.5   494.1 1025.22   504.6 1032.26
#Mann= 5 ,-1,0
       0      .1       0     330     .06       0  342.63    .045       0
   355.3     .06       0     430      .1       0
Bank Sta=342.63,355.3
XS Rating Curve= 0 ,0
Exp/Cntr(USF)=0,0
Exp/Cntr=0.3,0.1

Type RM Length L Ch R = 1 ,32193   ,112.3,109.2,104.8
XS GIS Cut Line= 2
 1685505.8088067399191.0601121491685413.33732328399690.112562375
#Sta/Elev= 30
       0  996.84    42.2  980.72    58.5  975.94    66.6  974.49   111.3   970.3
     140  966.21   160.2  963.34   217.1  961.33   318.8  961.37   326.9  960.88
  333.63 957.821   339.2     957   344.3  957.82   355.4  960.31   363.6  963.47
   379.8  974.63   383.9  976.03   396.1  976.75   408.3  976.39   412.4  978.82
   416.4  982.39   424.6  991.79   428.3  995.16   444.9 1005.75   453.1 1008.71
   465.3 1009.89   473.4  1013.1   493.5 1018.55   497.8 1020.51   507.5 1026.87
#Mann= 5 ,-1,0
       0      .1       0     140     .05       0  333.63    .045       0
   344.3     .06       0     440      .1       0
Bank Sta=333.63,344.3
XS Rating Curve= 0 ,0
Exp/Cntr(USF)=0,0
Exp/Cntr=0.3,0.1

Type RM Length L Ch R = 1 ,32083   ,44.2,43.5,44.7
BEGIN DESCRIPTION:
Structure XS 3
END DESCRIPTION:
XS GIS Cut Line= 4
1685309.12342926399179.3177015561685322.33364118399478.749171691
1685360.49647561399565.3494498181685350.22186634399679.837953105
#Sta/Elev= 30
       0 1004.35     5.2 1002.71    57.3  981.35    69.2  975.36    89.3  970.95
   109.3  969.32   129.3  968.89   213.4  960.02   261.5  959.82   307.6  960.69
   319.2  959.86   327.9  957.22   332.3  956.61   341.3957.2533   362.9  963.37
   380.4  966.12   393.5   974.7   397.6  975.89   409.6  976.73   421.7  975.92
   425.7  976.41   429.7  978.74   433.7  981.92   445.8  993.78   449.2  996.44
   461.8  1003.9   469.8 1007.32   485.7 1012.28     498  1014.4   509.3 1018.38
#Mann= 5 ,-1,0
       0      .1       0     150     .05       0   327.9    .045       0
   341.3     .05       0  454.36     .06       0
Bank Sta=327.9,341.3
XS Rating Curve= 0 ,0
Exp/Cntr(USF)=0,0
Exp/Cntr=0.3,0.1

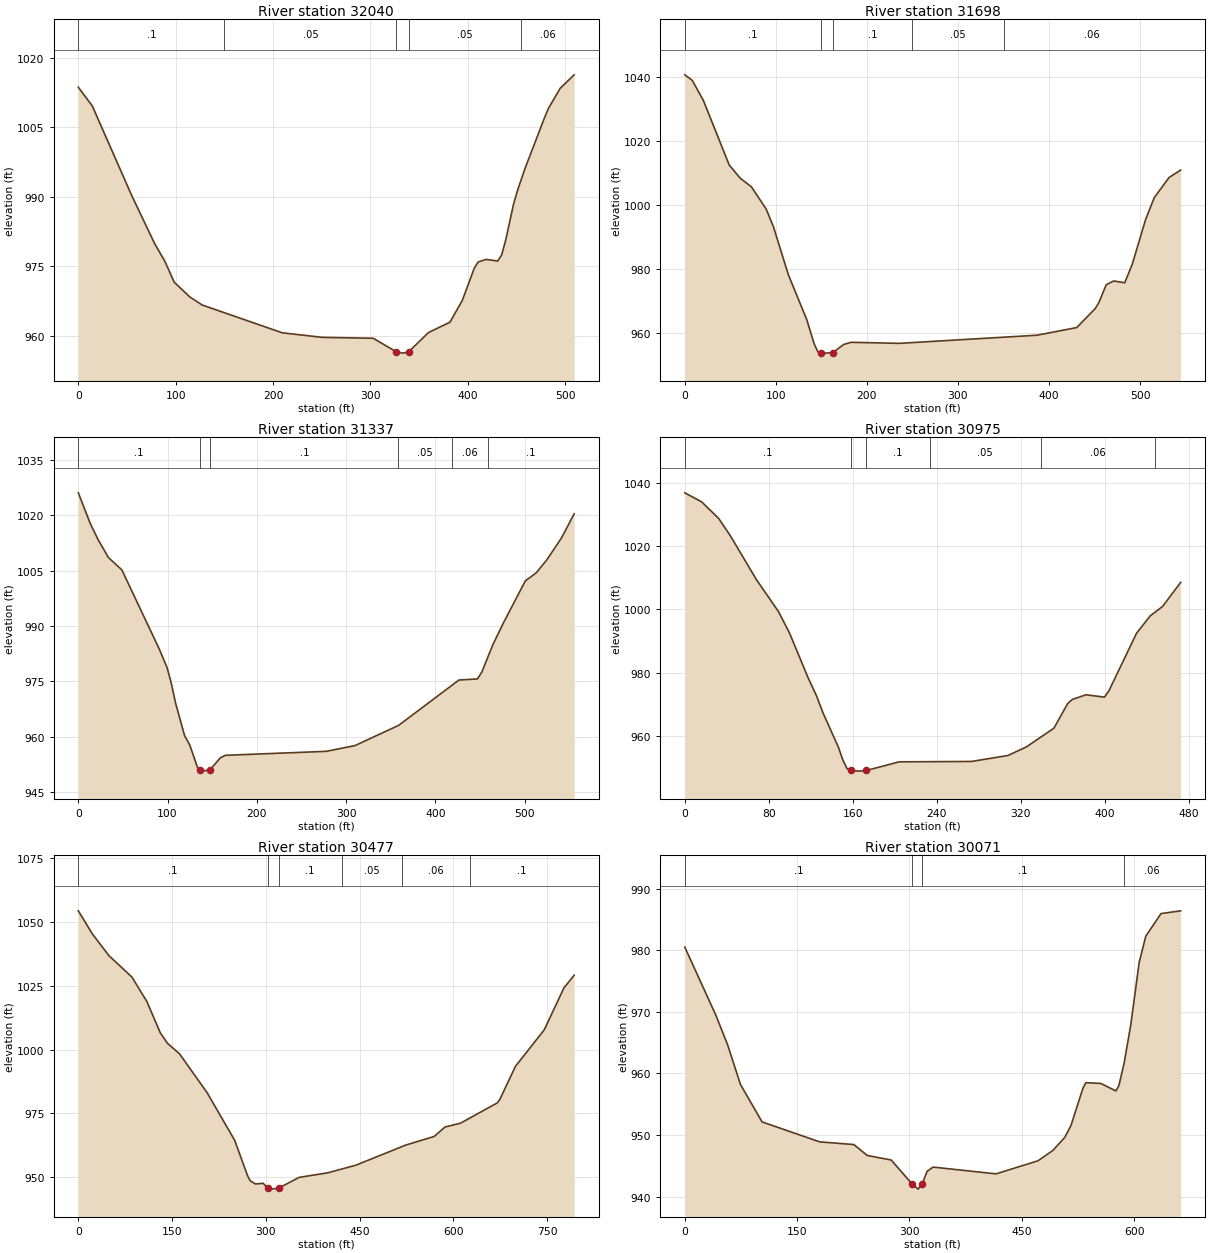
Type RM Length L Ch R = 1 ,32040   ,340.7,342.3,342
BEGIN DESCRIPTION:
Structure XS 2
END DESCRIPTION:
XS GIS Cut Line= 4
 1685265.8232902399174.1803969211685279.03350212399473.611867056
1685317.19633655399560.2121451841685306.92172728399674.700648471
#Sta/Elev= 30
       0 1013.61    14.4 1009.55    54.4  990.46    78.4  979.87    88.8  976.12
    98.5  971.56   114.5  968.39   127.2  966.65   209.5  960.65   250.6  959.67
   302.9  959.47   326.8  956.54   333.5  956.27   339.2  956.54   359.7  960.71
   381.8  962.95   394.4  967.64   406.7  974.58   410.7  975.92   418.8  976.48
   430.8  976.13   434.8  977.42   438.9  980.57   446.9  988.25   450.9  991.21
   458.9  996.13     479 1007.11     483 1009.09   495.1 1013.41   509.3 1016.28
#Mann= 5 ,-1,0
       0      .1       0     150     .05       0   326.8    .045       0
   339.2     .05       0  454.36     .06       0
Bank Sta=326.8,339.2
XS Rating Curve= 0 ,0
Exp/Cntr(USF)=0,0
Exp/Cntr=0.3,0.1

Type RM Length L Ch R = 1 ,31698   ,363.3,360.2,357.7
BEGIN DESCRIPTION:
Structure XS 1
END DESCRIPTION:
XS GIS Cut Line= 2
1684987.26758036399176.4654259891685080.00683478399712.966346417
#Sta/Elev= 30
       0 1040.73     8.2 1039.01    20.4 1032.74    48.8 1012.58      61 1008.42
    73.1 1005.79    89.4  998.82    97.5  993.17   113.7  978.35     134  964.25
   142.1  956.72   146.2  954.25   149.6  953.97   154.3  953.85   162.4     954
   174.6  956.56   182.7  957.23   235.5   956.9   386.8  959.44   430.4  961.83
   450.7  967.75   454.7  969.63   462.8   975.2     471  976.37   483.1  975.82
   491.3  981.52   506.1  995.61   515.6 1002.42   531.8 1008.68   544.5 1010.99
#Mann= 5 ,-1,0
       0      .1       0   149.6    .045       0   162.4      .1       0
     250     .05       0     350     .06       0
Bank Sta=149.6,162.4
XS Rating Curve= 0 ,0
Exp/Cntr(USF)=0,0
Exp/Cntr=0.3,0.1

Type RM Length L Ch R = 1 ,31337   ,359.5,362,364.1
XS GIS Cut Line= 3
1684588.02987681399321.6978353021684750.51548339399535.703268369
1684799.39326749399818.401803408
#Sta/Elev= 30
       0 1026.15    13.4 1017.79    22.1 1013.47    33.7 1008.59    48.8 1005.22
    90.6  983.79    99.4  978.73     104  974.64     109  969.04   119.1  960.21
   124.8  957.73   133.4  951.71   136.3  950.98   139.1   950.6   147.7  950.98
   159.1  954.21   164.8  954.89   277.7  955.97   310.1  957.54   358.9  963.02
   426.5  975.33   447.3  975.63   452.2  977.54   464.4  984.86   476.6  990.97
   500.9 1002.24   513.2 1004.45   525.3 1008.06   541.5 1013.95   555.6 1020.45
#Mann= 6 ,-1,0
       0      .1       0   136.3    .045       0   147.7      .1       0
   358.7     .05       0   418.7     .06       0   458.7      .1       0
Bank Sta=136.3,147.7
XS Rating Curve= 0 ,0
Exp/Cntr(USF)=0,0
Exp/Cntr=0.3,0.1

Type RM Length L Ch R = 1 ,30975   ,498,498.5,497.5
XS GIS Cut Line= 6
1684310.46686406399400.6222909991684327.34971701399512.659934178
1684353.26173867399609.244386673 1684381.9657495399679.205204755
1684417.96370901399760.1656727491684456.33272676 399846.98734951
#Sta/Elev= 30
       0  1036.8    16.1 1033.94    32.3 1028.71    43.6 1023.15    68.2 1009.45
    89.3  999.32    99.8  992.55   117.3  978.61   125.6  972.69   131.7  967.38
   146.3  956.61   150.4  952.71   154.6  949.79   158.7  949.23   166.1  949.02
  173.11 949.225   204.3  951.95   273.2  952.07   307.9  953.95   325.4  956.65
   351.7  962.57   364.8  970.33   369.2  971.63   382.3   973.1   399.8  972.36
   404.2  974.43   430.4   992.5   443.5  998.02   455.3 1000.99   472.4 1008.54
#Mann= 6 ,-1,0
       0      .1       0   158.7    .045       0  173.11      .1       0
   233.3     .05       0  338.92     .06       0  447.53      .1       0
Bank Sta=158.7,173.11
XS Rating Curve= 0 ,0
Exp/Cntr(USF)=0,0
Exp/Cntr=0.3,0.1

Type RM Length L Ch R = 1 ,30477   ,401.8,405.8,405
XS GIS Cut Line= 6
1683852.28734693399311.651149839  1683839.397937399407.490525082
1683834.61612242 399496.854847671683869.49761434399668.343677923
1683948.65561999399942.5777954351684060.69088618400037.260347605
#Sta/Elev= 30
       0 1054.29    22.3 1045.31    49.3 1036.66    85.7  1028.4   109.8 1018.73
   131.2 1006.52   142.6 1002.47   161.8  998.38   206.1  983.11   250.1  964.53
   271.1  950.47   275.2  948.62   283.4  947.39   295.7  947.67   303.4  945.75
   308.1  945.38   320.4  945.75   353.3  949.98   399.1  951.76   443.9  954.73
   524.1  962.63   569.5     966   586.8   969.7   611.4  971.17   670.5  979.13
   674.6  980.53   699.4  993.41   745.6 1007.74     777 1024.11   793.4  1029.1
#Mann= 6 ,-1,0
       0      .1       0   303.4    .045       0   320.4      .1       0
  421.32     .05       0  517.55     .06       0  626.56      .1       0
Bank Sta=303.4,320.4
XS Rating Curve= 0 ,0
Exp/Cntr(USF)=0,0
Exp/Cntr=0.3,0.1

Type RM Length L Ch R = 1 ,30071   ,223.3,226.2,225
XS GIS Cut Line= 3
1683447.80560113399354.0713908771683534.08570044 399563.36470107
1683528.10589158399999.036489636
#Sta/Elev= 30
       0  980.52    41.6  969.43    57.3  964.62    74.3  958.22   103.2  952.13
   180.1  948.89   225.8  948.45   243.6  946.68   275.6  945.94   303.6  942.04
   311.6  941.21   316.9 942.035   323.6  944.11   331.6  944.79   415.6  943.69
   471.6  945.81   491.6   947.5   507.6  949.65   515.6  951.52   531.6  957.58
   535.6   958.5   555.6  958.38   575.6  957.16   579.6  958.01   586.6  961.63
   595.6  967.96   606.8  978.07   615.6   982.3   635.9  985.97   662.1  986.42
#Mann= 4 ,-1,0
       0      .1       0   303.6    .045       0   316.9      .1       0
  586.38     .06       0
Bank Sta=303.6,316.9
XS Rating Curve= 0 ,0
Exp/Cntr(USF)=0,0
Exp/Cntr=0.3,0.1

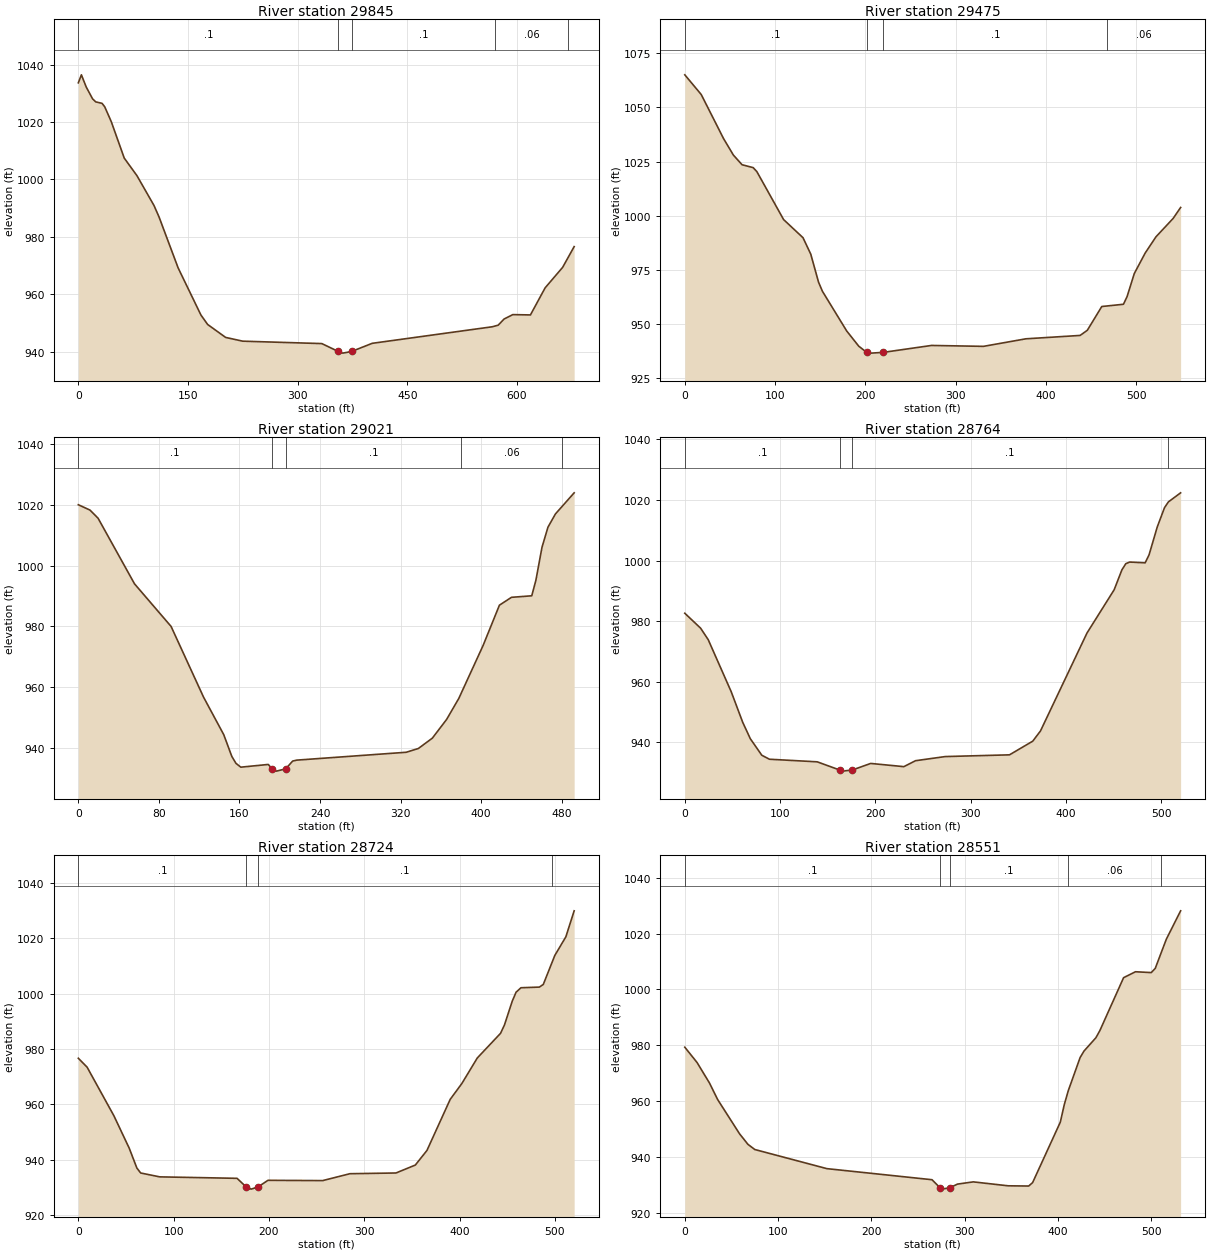
Type RM Length L Ch R = 1 ,29845   ,373.4,370.2,363.6
BEGIN DESCRIPTION:
Low water crossing
END DESCRIPTION:
XS GIS Cut Line= 6
1683317.57816001399390.3341956361683396.22237027399578.040675531
1683349.75595971399643.3840653841683332.33105575399680.411986301
1683327.24879209399698.562927927 1683302.7976871 400024.14504616
#Sta/Elev= 30
       0 1033.63     4.2 1036.41    10.8 1032.17    19.5 1028.05    23.8    1027
    32.5 1026.48    36.2 1025.24    45.1 1020.09    62.8 1007.44    80.2 1001.32
   103.5  990.95   110.5   986.9   136.5  969.24   167.7  952.84   176.9  949.54
   201.5  945.04   224.9  943.73   333.1  942.89  355.63940.1486   361.8  939.57
   373.8  940.14     402  942.98   566.3  948.74   574.4   949.3   582.4  951.43
   594.4  952.97   618.5  952.86   638.6  962.29   662.5   969.4   678.3  976.63
#Mann= 5 ,-1,0
       0      .1       0  355.63    .045       0   373.8      .1       0
  569.97     .06       0  669.97      .1       0
Bank Sta=355.63,373.8
XS Rating Curve= 0 ,0
Exp/Cntr(USF)=0,0
Exp/Cntr=0.3,0.1

Type RM Length L Ch R = 1 ,29475   ,449.8,454.1,456.6
XS GIS Cut Line= 6
1682965.31996076399474.7607317571682985.39275526399561.816331923
1683012.99670267399632.1787240061683060.34109618399720.266474336
1683068.91686642399805.3447162511683075.19113208400003.775749832
#Sta/Elev= 30
       0 1065.08    18.2 1055.97    42.9 1035.61    53.8 1027.98    63.4 1023.51
    75.7 1022.17    79.8 1020.32   109.4  998.16   130.9  989.77   139.5  982.15
   148.1  969.21   152.4     965   179.3  946.63   192.6  939.63  201.49936.7243
   206.2  936.41   219.8  936.76   273.2  939.96   330.7  939.54   377.7  943.03
   437.7  944.59   445.7  946.97   461.7  957.96   485.7     959   489.7  962.53
   497.7   973.2   509.7  982.65   521.7  990.18   540.7  998.68     549 1003.75
#Mann= 4 ,-1,0
       0      .1       0  201.49    .045       0   219.8      .1       0
   467.8     .06       0
Bank Sta=201.49,219.8
XS Rating Curve= 0 ,0
Exp/Cntr(USF)=0,0
Exp/Cntr=0.3,0.1

Type RM Length L Ch R = 1 ,29021   ,261.1,256.5,251.6
BEGIN DESCRIPTION:
Structure XS 4
END DESCRIPTION:
XS GIS Cut Line= 2
1682567.13564874399537.0412913821682621.49866074400026.308399446
#Sta/Elev= 30
       0 1020.06    11.6 1018.29    19.6 1015.62    55.8     994    92.1  979.98
   124.3  956.72   144.4  944.33   152.4  937.17   156.5   934.9   161.3  933.63
   188.6  934.53   192.4  933.08   196.7  932.33  205.86933.0726   212.8  935.64
   216.8  935.95   325.5  938.54   337.6  939.78   351.5  943.19   365.7  949.37
   377.8  956.29     402  973.79   418.1  986.98   430.1  989.57   450.2  990.07
   454.3  995.18   460.4 1006.09   466.3 1012.67   473.7 1017.02   492.3 1023.98
#Mann= 5 ,-1,0
       0      .1       0   192.4    .045       0  205.86      .1       0
     380     .06       0     480      .1       0
Bank Sta=192.4,205.86
XS Rating Curve= 0 ,0
Exp/Cntr(USF)=0,0
Exp/Cntr=0.3,0.1

Type RM Length L Ch R = 1 ,28764   ,40,40.4,40.4
BEGIN DESCRIPTION:
Structure XS 3
END DESCRIPTION:
XS GIS Cut Line= 4
1682305.17841488399579.9880708681682313.98522282399698.879978127
 1682457.8297526399819.2396867111682495.99258702400029.135276071
#Sta/Elev= 30
       0  982.61    16.6  977.67    24.6  973.86    48.7  956.68    60.7  946.63
    68.7  941.18    80.8   935.7    88.8  934.39   138.9  933.53  162.49930.8276
   165.4  930.46   175.9  930.85     195     933   229.8  931.94     242   933.9
   273.2  935.27   340.6  935.84     365  940.36   373.1  943.73   421.9  976.08
   450.4  990.37   458.5  996.93   462.6  998.98   466.7  999.51   482.9  999.26
     487  1001.9   495.6 1011.12   503.2 1017.48   507.3 1019.39   520.1 1022.38
#Mann= 4 ,-1,0
       0      .1       0  162.49    .045       0   175.9      .1       0
  506.77     .06       0
Bank Sta=162.49,175.9
XS Rating Curve= 0 ,0
Exp/Cntr(USF)=0,0
Exp/Cntr=0.3,0.1

Type RM Length L Ch R = 1 ,28724   ,169.1,172.5,175.5
BEGIN DESCRIPTION:
Structure XS 2
END DESCRIPTION:
XS GIS Cut Line= 4
 1682258.2087725399587.3270774891682267.01558045399706.218984748
1682410.86011022399826.5786933321682449.02294465400036.474282692
#Sta/Elev= 30
       0  976.66     9.2  973.44    37.3  955.89    53.4  944.16    61.4     937
    65.4  935.21    85.4  933.81   166.5  933.28  176.15930.1519   181.3  929.38
   188.5  930.16   198.9  932.56   256.3  932.46   284.9  934.95   333.2  935.21
   353.5  938.08   365.7  943.36   390.1  961.82   402.3  967.53   418.5  976.76
   442.9  985.67     447   988.7   455.1  997.22   459.2 1000.53   464.3 1002.13
   483.6 1002.37   487.7 1003.31   499.8 1013.79   511.4 1020.54   520.1 1029.92
#Mann= 4 ,-1,0
       0      .1       0  176.15    .045       0   188.5      .1       0
  496.77     .06       0
Bank Sta=176.15,188.5
XS Rating Curve= 0 ,0
Exp/Cntr(USF)=0,0
Exp/Cntr=0.3,0.1

Type RM Length L Ch R = 1 ,28551   ,557.4,556.4,549.7
BEGIN DESCRIPTION:
Structure XS 1
END DESCRIPTION:
XS GIS Cut Line= 3
1682134.39507788399536.6743839981682091.59399127399627.626693051
1682233.90760426400034.237015879
#Sta/Elev= 30
       0   979.3    13.1  973.83    26.4  966.49    35.2  960.54    58.7  948.24
    67.7  944.46      75  942.62   152.3  935.76   264.9  931.79  273.44928.9241
   275.2  928.42   283.7  928.88   292.2  930.22   309.1  931.02   346.5  929.61
   368.5  929.53   372.7  930.75   402.4  952.44   406.6  958.68   410.9  963.69
   423.6  975.58   427.8  977.93   440.5  982.68   444.8  985.27   470.2 1004.22
   482.9 1006.34   499.8 1006.04   504.1 1007.54     516 1018.02   531.3 1028.18
#Mann= 5 ,-1,0
       0      .1       0  273.44    .045       0   283.7      .1       0
  410.52     .06       0  510.52      .1       0
Bank Sta=273.44,283.7
XS Rating Curve= 0 ,0
Exp/Cntr(USF)=0,0
Exp/Cntr=0.3,0.1

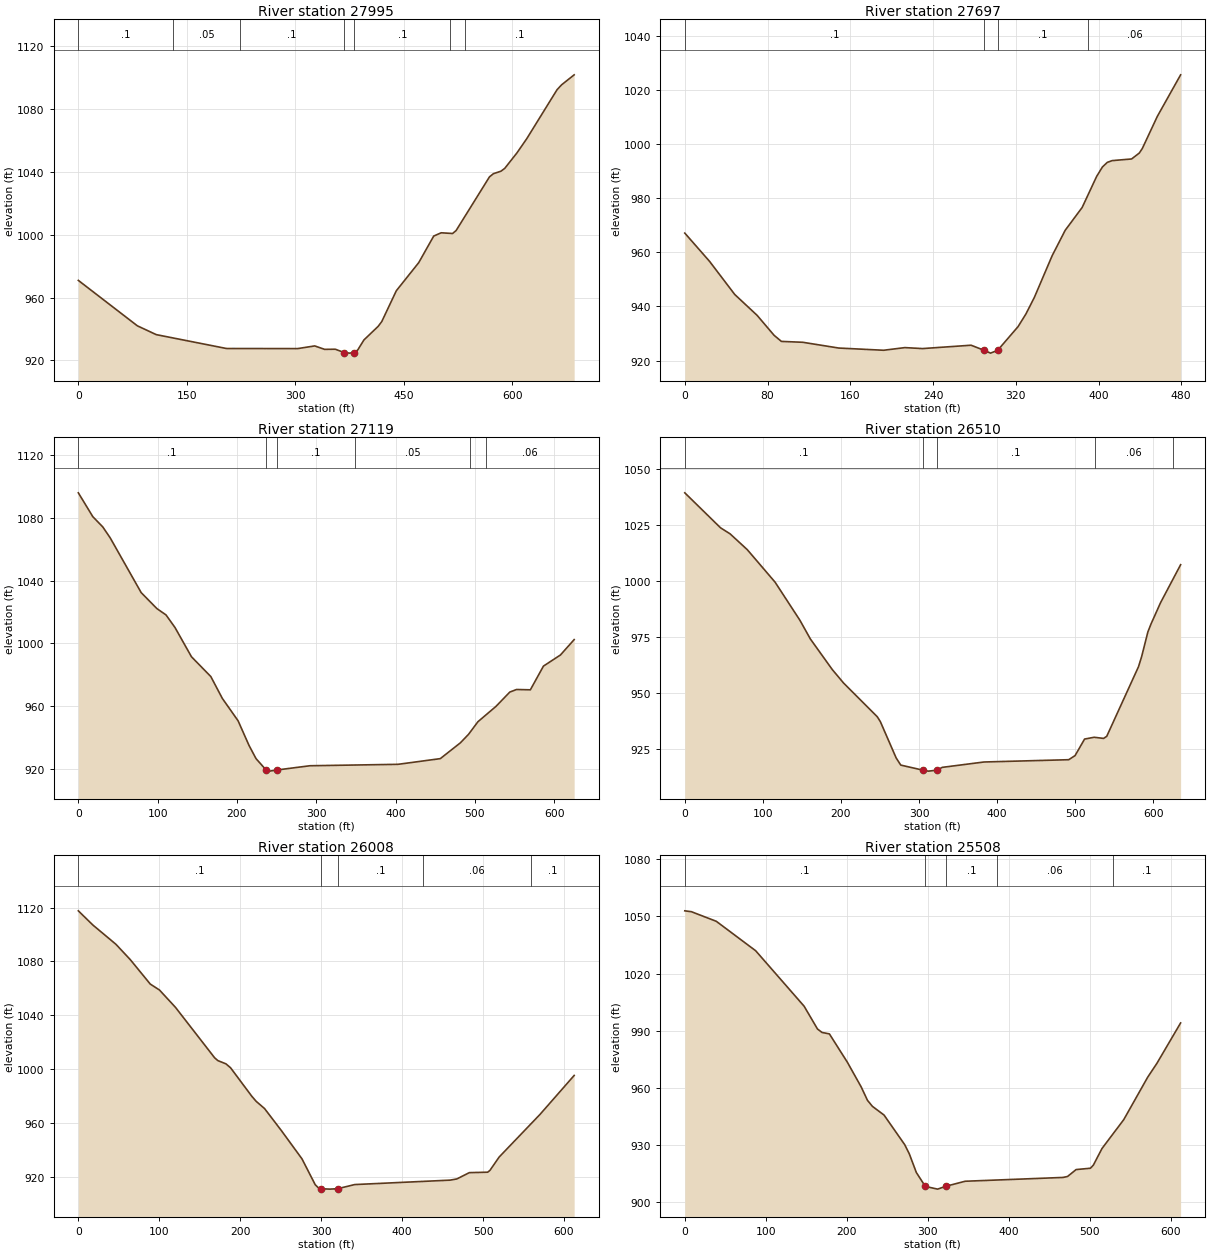
Type RM Length L Ch R = 1 ,27995   ,295,298.2,300.4
XS GIS Cut Line= 6
1681548.10658784399758.2647579161681612.81643218399848.482753336
1681693.49802934399910.4970650081681773.96538809 399961.72366859
1681872.06755409400032.5401280081682034.17320101400230.910466179
#Sta/Elev= 30
       0  970.93    81.6  941.99   107.7  936.38   204.7  927.55   303.1  927.48
   326.7  929.19   340.4     927   355.2  927.08  367.46924.9652   374.8   924.6
   381.3  924.96   386.2  926.63   394.8  933.02   414.4  941.65   419.4   944.7
   439.5  964.32   470.5  982.24   491.2  999.16   501.5 1001.24   517.3  1000.8
   522.1 1002.64   568.3 1036.89   573.8  1038.9   584.1 1040.47   589.3 1042.24
   606.2 1052.11   619.7 1061.11   661.6 1092.33     668 1095.51   685.3 1101.85
#Mann= 7 ,-1,0
       0      .1       0  131.03     .05       0  222.79      .1       0
  367.46    .045       0   381.3      .1       0  514.16     .06       0
  534.16      .1       0
Bank Sta=367.46,381.3
XS Rating Curve= 0 ,0
Exp/Cntr(USF)=0,0
Exp/Cntr=0.3,0.1

Type RM Length L Ch R = 1 ,27697   ,574.7,578,567.9
XS GIS Cut Line= 2
1681414.73651972399885.0477389821681666.78736311400292.846980883
#Sta/Elev= 30
       0  967.08    23.9  956.66    48.3   944.4    69.9   936.7    86.3  929.33
    93.4  927.06     114  926.74   148.8  924.61   192.2  923.79   212.8  924.77
   229.8  924.41   276.8  925.65   289.7  923.73   295.6  922.73  302.42923.7354
   322.2  932.51   329.8  937.18     338  943.34   355.2  958.73   367.8  968.12
   384.2  976.55   398.2  988.02   403.8  991.52   408.5  993.21   413.2  993.86
     432  994.47   439.5  996.68   442.4  998.37   456.9 1010.22   479.4 1025.56
#Mann= 4 ,-1,0
       0      .1       0   289.7    .045       0  302.42      .1       0
     390     .06       0
Bank Sta=289.7,302.42
XS Rating Curve= 0 ,0
Exp/Cntr(USF)=0,0
Exp/Cntr=0.3,0.1

Type RM Length L Ch R = 1 ,27119   ,610.4,608.3,607.9
XS GIS Cut Line= 6
1681007.36697824400022.1160408231681068.91836433 400100.77795699
 1681128.1905555 400172.615739821681180.56938775400227.307231483
1681249.01380466400300.224736568  1681421.983275400489.289975238
#Sta/Elev= 30
       0 1095.98    18.3 1080.75    30.8 1074.24    40.2 1067.23    79.2 1032.35
    99.1 1022.11   110.5 1018.12   121.9 1010.04   142.6  991.43     167  978.79
   181.5  964.87   201.4  950.56   215.1  934.93     224  926.44  236.64919.2386
     241  918.47   250.7  919.22   291.9   921.9     403  922.81   456.3  926.44
   481.6  936.53   491.9  941.96   503.7  949.98   526.4  959.74   543.9   968.9
   552.4  970.54   569.8  970.33   586.3  985.46   607.7  992.54     625 1002.36
#Mann= 6 ,-1,0
       0      .1       0  236.64    .045       0   250.7      .1       0
  348.74     .05       0  493.75      .1       0  513.75     .06       0
Bank Sta=236.64,250.7
XS Rating Curve= 0 ,0
Exp/Cntr(USF)=0,0
Exp/Cntr=0.3,0.1

Type RM Length L Ch R = 1 ,26510   ,501.3,502.8,500.1
XS GIS Cut Line= 6
1680504.32652317400255.697162002 1680586.8394815400424.088229418
1680629.75343767400488.9785195891680703.61811934 400556.96296367
1680725.80929019400601.0559029371680762.38189775400817.780801096
#Sta/Elev= 30
       0 1039.49    45.8 1023.86      58 1021.17      80 1014.11   115.7  999.55
   147.4  982.58   160.9  974.17   188.9  960.54   203.3  954.55   246.6  939.43
   250.5  937.25   270.7  921.06   276.6  917.87  304.96915.6115   312.1  915.18
     323  915.61   329.7  916.86   383.2  919.26   491.7  920.28   499.8  922.11
     512   929.5   524.3  930.31   536.3  929.79   540.4  930.74     581  961.78
     585  966.23   593.1   977.4   597.2     981   609.3  990.42     635 1007.38
#Mann= 5 ,-1,0
       0      .1       0  304.96    .045       0     323      .1       0
  525.16     .06       0  625.16      .1       0
Bank Sta=304.96,323
XS Rating Curve= 0 ,0
Exp/Cntr(USF)=0,0
Exp/Cntr=0.3,0.1

Type RM Length L Ch R = 1 ,26008   ,499,500,501.8
XS GIS Cut Line= 6
1680024.00825809400579.3530107591680095.95529267400639.517916679
1680162.97320326400695.821281761  1680220.133522400744.401565179
1680295.00837226400810.6868656721680486.83344792400980.590397254
#Sta/Elev= 30
       0 1117.59      18 1107.03    46.4 1092.78    64.2 1081.35    88.9 1063.21
   100.3 1058.79   120.1 1045.88   168.4 1008.49   172.4  1006.4   182.4 1003.98
   188.1 1001.07   214.3  979.96   219.6  976.24   230.1   970.8   251.1  954.26
   276.3  933.48   292.7  914.26   296.1  912.22  299.93911.2902   310.8  910.99
   320.4   911.3   341.4  914.37   459.3  917.66   467.7  918.56   483.1  923.23
   505.8  923.56   508.6  924.94   519.9  934.79   570.3  966.39   612.6  995.37
#Mann= 5 ,-1,0
       0      .1       0  299.93    .045       0   320.4      .1       0
  426.33     .06       0  558.83      .1       0
Bank Sta=299.93,320.4
XS Rating Curve= 0 ,0
Exp/Cntr(USF)=0,0
Exp/Cntr=0.3,0.1

Type RM Length L Ch R = 1 ,25508   ,501.4,500.9,500.8
XS GIS Cut Line= 6
1679705.30745192400907.8418550941679768.54092126400977.069406927
1679826.60215685401042.5305620881679876.36944576401098.639373749
 1679942.7249561401173.4522162531680112.76168951401365.159181923
#Sta/Elev= 30
       0 1052.95     8.1  1052.5    38.9 1047.46    87.6    1032   147.4 1002.93
   163.9  990.98   169.6  989.15   178.6  988.42   200.8  973.57   217.8  960.67
   225.7  953.55   231.8  950.39   246.1  945.86   271.6  930.36   277.3  925.55
     286  915.74   297.1  908.43   312.3     907   322.2  908.46   346.3  911.13
   467.3  913.13   472.8  913.63   483.4  917.25   501.1  917.96   504.7  919.59
   515.4  928.32   542.2  943.41   571.9  965.75   583.3  973.03   612.5  994.16
#Mann= 5 ,-1,0
       0      .1       0   297.1    .045       0   322.2      .1       0
  386.26     .06       0  528.76      .1       0
Bank Sta=297.1,322.2
XS Rating Curve= 0 ,0
Exp/Cntr(USF)=0,0
Exp/Cntr=0.3,0.1