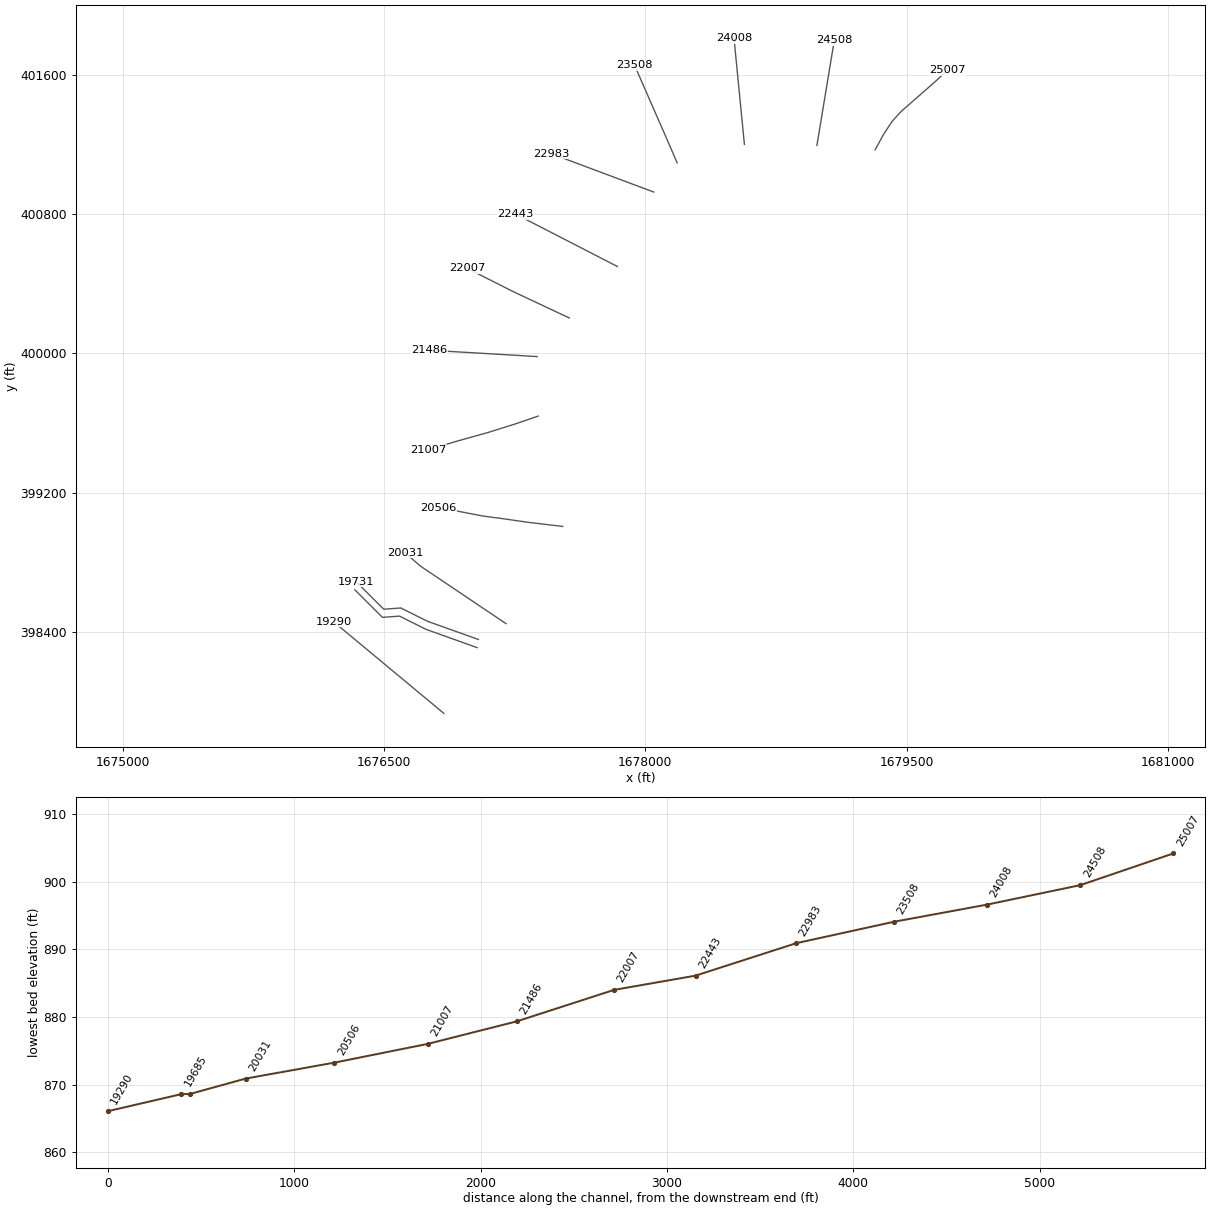
HEC-RAS study WILLEYFK.prj: WILLEYFK

--- WILLEYFK.g01 (geometry) --- (continued)

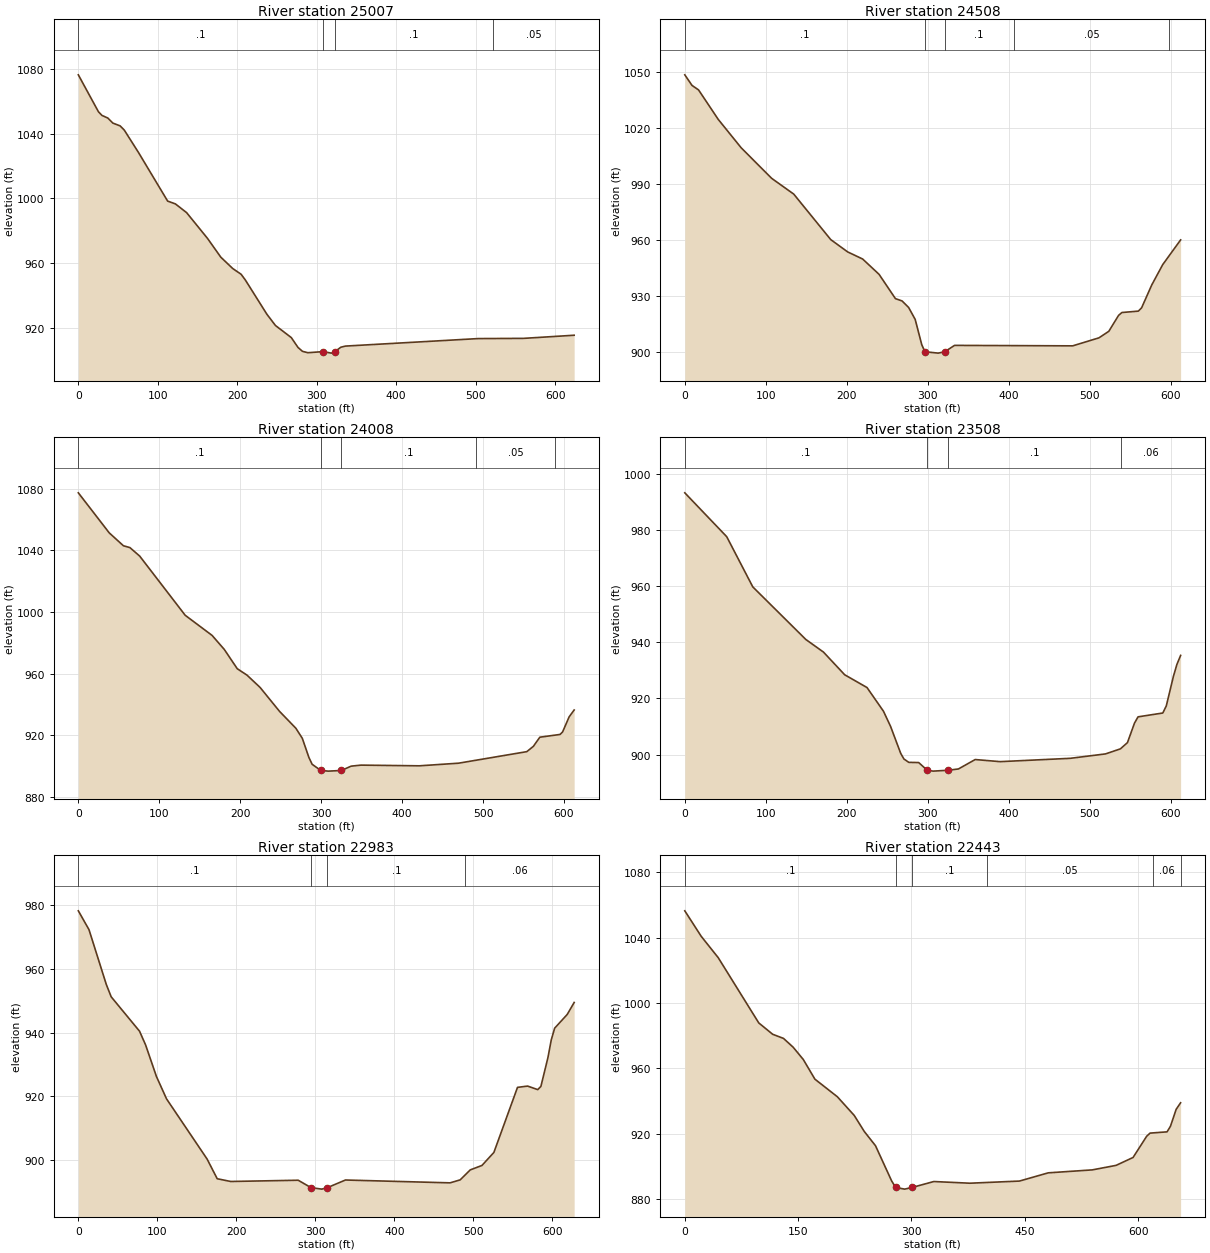
Type RM Length L Ch R = 1 ,25007   ,492.6,499.1,502.2
XS GIS Cut Line= 6
1679320.00999418401170.3272225111679367.18509668401257.267665416
1679417.40087551401333.9787980911679468.33351642401389.994762167
1679666.45254275401563.4018956721679734.69125143401628.544810012
#Sta/Elev= 30
       0 1076.57    25.3 1053.71    29.8 1051.41    37.1 1049.81    43.5 1046.66
    52.6 1044.95    57.8 1042.36    75.7 1028.48   112.4  998.36   122.2  996.61
   136.3  991.19   162.6  975.23   179.3  963.62   194.3  956.59   204.9  953.02
   210.3   949.4   237.3  928.27   248.1  921.29     268  913.82   276.5  907.68
   282.1  905.29   288.8  904.44     308  905.11   318.5  904.18  322.95 905.155
   330.4  907.84   336.1  908.54   503.3  913.19   560.2  913.32     624  915.26
#Mann= 4 ,-1,0
       0      .1       0     308    .045       0  322.95      .1       0
  521.74     .05       0
Bank Sta=308,322.95
XS Rating Curve= 0 ,0
Exp/Cntr(USF)=0,0
Exp/Cntr=0.3,0.1

Type RM Length L Ch R = 1 ,24508   ,497.4,500,503.8
XS GIS Cut Line= 6
 1678985.4962275 401195.781896011679015.08606334401374.600107923
1679027.32947718401448.5940544161679043.65424767401547.252649754
1679070.18240984401707.5725390911679085.48684117401800.065136254
#Sta/Elev= 30
       0 1048.31     8.9 1042.66      17 1040.24    41.3 1024.49    69.7 1009.27
   107.3  992.96   134.6  984.52   180.3  960.19   201.2  953.61   219.7  949.82
     240  941.62   260.2  928.64   268.4  927.39   276.5  923.91   284.6  917.53
   292.7  904.04  296.61900.2372     313  899.49   321.1  900.21   333.2  903.63
   479.2  903.38   511.6  907.66   523.8  911.16   535.9   919.7     540   921.2
   560.3  921.96   564.3  923.72   576.9     936   590.4  946.83   612.5  960.04
#Mann= 5 ,-1,0
       0      .1       0  296.61    .045       0   321.1      .1       0
  406.25     .05       0  598.75      .1       0
Bank Sta=296.61,321.1
XS Rating Curve= 0 ,0
Exp/Cntr(USF)=0,0
Exp/Cntr=0.3,0.1

Type RM Length L Ch R = 1 ,24008   ,496.9,500,504.9
XS GIS Cut Line= 6
1678569.17356934401201.137200251  1678560.050228401294.442131758
1678551.53580934401381.5269313451678527.20744592401630.340410084
1678518.69269918401717.4252096711678509.56935784401810.730141178
#Sta/Elev= 30
       0 1077.47    38.2 1051.44    55.7 1043.07    63.7 1041.88    75.8 1036.36
     132   997.9   165.2  984.83   180.3   975.7   196.3  963.18   208.4  958.97
   224.5  951.02   248.6  935.42   268.7  924.49   276.7  917.92   284.8  905.54
   288.8  901.08  299.55 897.019   308.9  896.61   324.9  897.02     337  899.84
   349.1  900.51   421.3  900.06   469.6  901.76     554  909.27   562.1  912.71
   570.1  918.66   595.1  920.45   598.2  922.05   606.3  931.88   612.5  936.34
#Mann= 5 ,-1,0
       0      .1       0  299.55    .045       0   324.9      .1       0
  491.25     .05       0  588.75     .06       0
Bank Sta=299.55,324.9
XS Rating Curve= 0 ,0
Exp/Cntr(USF)=0,0
Exp/Cntr=0.3,0.1

Type RM Length L Ch R = 1 ,23508   ,514.7,524.5,531.1
XS GIS Cut Line= 6
1678182.68254443 401095.185312421678146.02448125401181.499444261
1678110.95335717401261.6633259211678080.89108133401330.374802679
 1678010.7465366 401490.70190984 1677938.0970756401656.755055428
#Sta/Elev= 30
       0  993.33    51.8  977.68      84  959.78   149.5  941.03   171.3  936.53
   197.5  928.44   225.1  923.88   245.5   915.4   254.3  909.96   266.7  900.42
   270.7  898.39   276.7   897.2   288.9  897.13  299.47894.3972   306.7  894.07
   325.3  894.38     338  894.84   358.7   898.2   389.6  897.45   476.3  898.64
   519.7  900.21   538.1  902.01   546.8  904.23   555.5  911.18   559.9  913.43
   590.5   914.8   594.8  917.33   603.6  927.88   607.9  932.12   612.5  935.34
#Mann= 4 ,-1,0
       0      .1       0  299.47    .045       0   325.3      .1       0
  538.78     .06       0
Bank Sta=299.47,325.3
XS Rating Curve= 0 ,0
Exp/Cntr(USF)=0,0
Exp/Cntr=0.3,0.1

Type RM Length L Ch R = 1 ,22983   ,538.9,539.9,532.3
XS GIS Cut Line= 2
1678048.72972821400927.5442900651677461.00427327401147.633947876
#Sta/Elev= 30
       0  978.25    13.5  972.34    35.4  955.14    41.6  951.26    77.5  940.46
    85.2  936.13    98.9  926.23   111.7  919.21     163  900.34   175.8  894.16
   192.9   893.3   278.3  893.69  294.56891.3632   308.2   890.9   315.1  891.35
   338.1  893.76   470.5  892.87   483.3   893.8   496.1  896.94   510.9  898.33
     526  902.42   555.9  922.84   568.7  923.24   581.5  922.13   585.5  923.14
   594.4  932.17   598.6  937.71   602.9  941.41   618.8  945.72   627.6  949.48
#Mann= 4 ,-1,0
       0      .1       0  294.56    .045       0   315.1      .1       0
     490     .06       0
Bank Sta=294.56,315.1
XS Rating Curve= 0 ,0
Exp/Cntr(USF)=0,0
Exp/Cntr=0.3,0.1

Type RM Length L Ch R = 1 ,22443   ,432.4,436.2,433.4
XS GIS Cut Line= 2
1677839.49762054 400499.998174561677256.14390306400800.555125015
#Sta/Elev= 30
       0 1056.36    21.8 1040.72    44.3 1027.66    97.9  987.78   116.3  980.84
   130.6  978.32   143.3  972.98   156.8  965.42   172.2  953.38   201.9  942.62
   224.3  931.16   237.5  921.41   252.4  912.66   273.8  891.08  279.16887.1012
     291   886.1   300.8  887.11   329.6  890.75   377.3  889.72   442.9  891.03
     481  896.06   539.3  897.87   570.8  900.63   593.3  905.47   611.3  918.45
   615.8  920.37   638.3  921.14   642.8  924.59   650.3   934.9   656.2  938.93
#Mann= 6 ,-1,0
       0      .1       0  279.16    .045       0   300.8      .1       0
     400     .05       0     620     .06       0  656.23      .1       0
Bank Sta=279.16,300.8
XS Rating Curve= 0 ,0
Exp/Cntr(USF)=0,0
Exp/Cntr=0.3,0.1

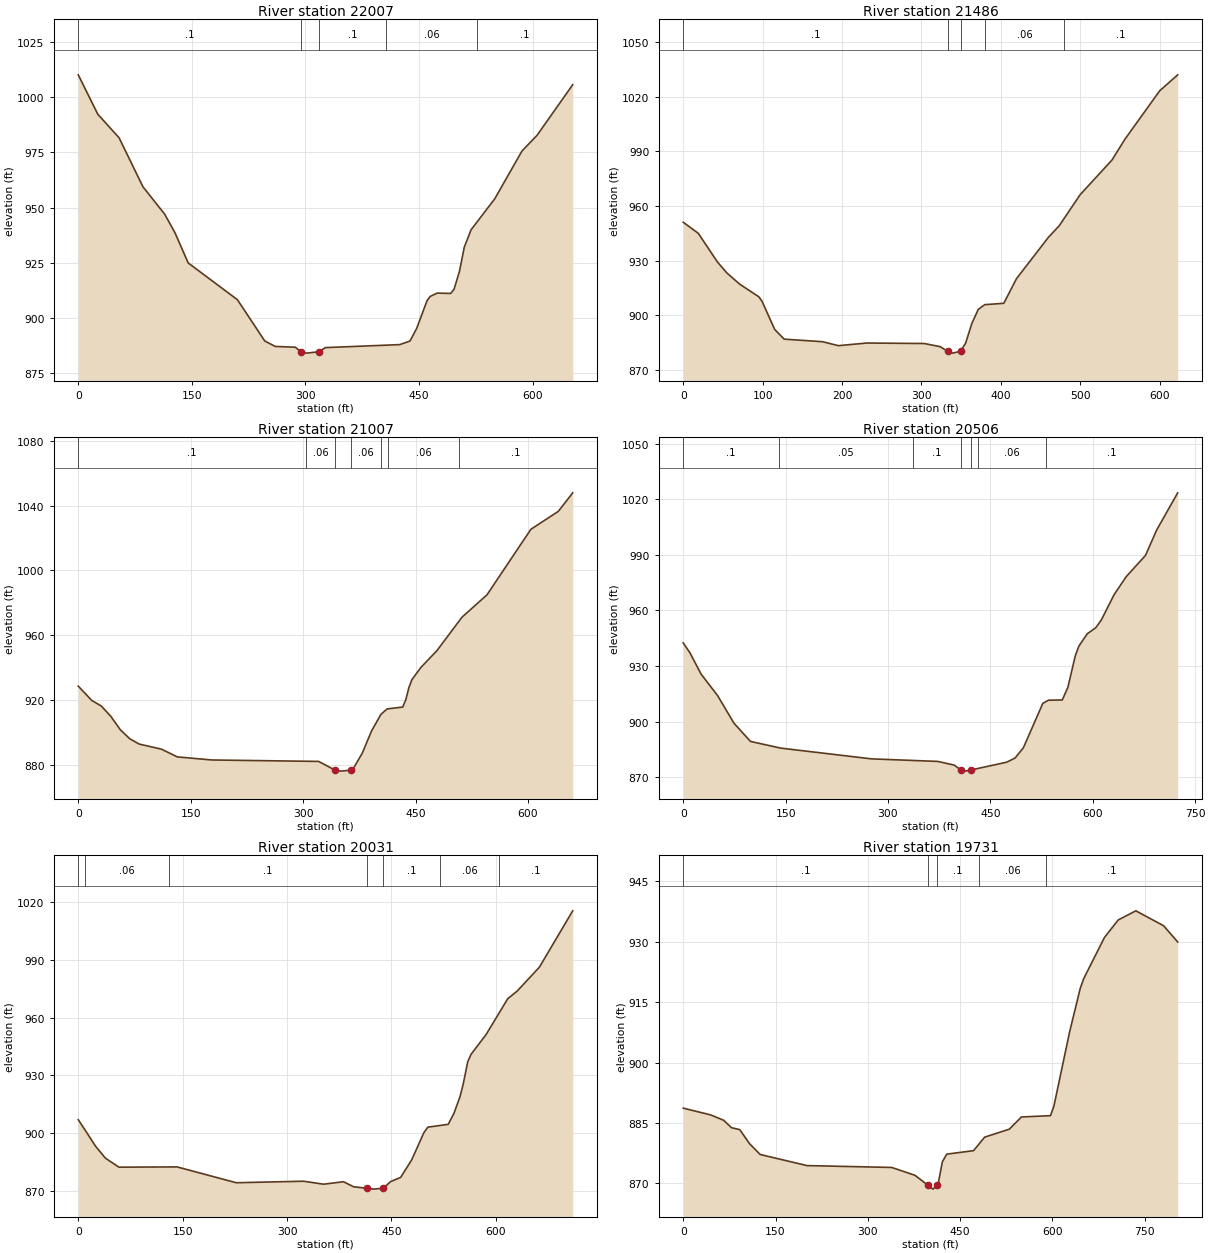
Type RM Length L Ch R = 1 ,22007   ,514.5,521.3,519.6
XS GIS Cut Line= 6
 1677563.4754495400204.1542860871677478.64983176400244.075138003
1677399.47840217400281.3332655881677331.61731742 400313.26889725
  1677241.135543400355.848536506 1676976.3121932400489.744664451
#Sta/Elev= 30
       0 1010.16    25.8   992.3    53.9  981.62    85.4  959.43   114.2  946.95
   127.5  938.73   145.2  924.88   210.2  908.21   246.3  889.51   260.1  887.04
   286.6  886.68  294.16884.6094   301.5     884   317.6  884.62   326.4   886.5
   424.6  887.86   438.1  889.48     447  895.26   460.5   907.7   464.7  909.69
   473.9  911.21   491.9  911.06   496.3  912.97   503.4  921.02   509.8  932.03
   518.8  939.94   550.1     954     586  975.63     606  982.79     653 1005.69
#Mann= 5 ,-1,0
       0      .1       0  294.16    .045       0   317.6      .1       0
  406.25     .06       0  526.25      .1       0
Bank Sta=294.16,317.6
XS Rating Curve= 0 ,0
Exp/Cntr(USF)=0,0
Exp/Cntr=0.3,0.1

Type RM Length L Ch R = 1 ,21486   ,474.6,478.7,481.2
XS GIS Cut Line= 2
1677379.09901916399982.220519003 1676757.4925989400019.107053832
#Sta/Elev= 30
       0  951.09      19  945.01    43.1  929.29    55.1  923.23    71.1  917.16
    95.2  910.24    99.2  907.82   115.2  892.33   127.2  887.01   175.3  885.62
   195.3  883.44   231.4  884.89   303.5  884.62   323.6   882.9  332.82880.4037
   339.6  879.35   349.2   880.4   355.6  884.77   363.6  895.77   371.6  903.33
   379.7  905.91   403.7  906.66   419.7  920.16   459.8  942.78   473.6  949.22
   499.9  966.21   539.9  985.16     556  996.42     600 1023.12   622.7 1031.89
#Mann= 5 ,-1,0
       0      .1       0  332.82    .045       0   349.2      .1       0
     380     .06       0     480      .1       0
Bank Sta=332.82,349.2
XS Rating Curve= 0 ,0
Exp/Cntr(USF)=0,0
Exp/Cntr=0.3,0.1

Type RM Length L Ch R = 1 ,21007   ,502.5,500.6,495.4
XS GIS Cut Line= 6
1677385.10721242399640.3912096321677251.88388109399594.649271503
1677096.76542492399545.9498938321676928.21228434399498.887323916
1676844.27347584399474.1455755081676754.97805075399445.563611671
#Sta/Elev= 30
       0  928.54      18  919.69    30.7  916.26    43.3  909.97      56  901.65
    68.7  896.01    81.4  892.72     111  889.58   132.2   884.8   178.4   882.9
   320.7  882.01   342.7  876.62   349.8  876.01   363.6  876.59   366.8  877.49
   378.9  887.09   391.3  900.83   403.8  911.08   412.1  914.46   432.9   915.6
     437  920.16   441.2  927.73   445.3  932.65   457.4  940.23   478.5  950.46
   511.9  971.11   545.3  984.95   603.9 1025.47   640.5 1036.56   659.7    1048
#Mann= 7 ,-1,0
       0      .1       0  303.44     .06       0   342.7    .045       0
   363.6     .06       0  403.44      .1       0  413.44     .06       0
  508.44      .1       0
Bank Sta=342.7,363.6
XS Rating Curve= 0 ,0
Exp/Cntr(USF)=0,0
Exp/Cntr=0.3,0.1

Type RM Length L Ch R = 1 ,20506   ,477.3,475.7,470.7
XS GIS Cut Line= 6
1677526.00339319399006.280587643  1677328.056629 399029.93747443
1677167.18949668399052.9161030051677068.04074484399065.980053261
1676905.40918034399097.4179825041676809.35687901 399111.01178734
#Sta/Elev= 30
       0  942.43      10  936.99    26.1  925.62    50.2  914.09    74.4  899.07
    98.6  889.26   142.9  885.65   276.1  879.85     373  878.48   397.2  876.48
406.7856873.8378   413.4  873.24421.3056873.8374     474  878.07   486.2  880.29
   498.4  885.84   526.9  909.81   535.1   911.5   555.4  911.63   563.6  918.41
   574.4  935.39   579.9  940.79   592.1  947.38   604.4  950.58   612.5   954.7
   631.4  968.49     649  978.14   677.4  989.67   693.5 1003.19   724.5  1023.4
#Mann= 7 ,-1,0
       0      .1       0     140     .05       0  336.86      .1       0
406.7856    .045       0421.3056      .1       0  431.86     .06       0
  531.86      .1       0
Bank Sta=406.7856,421.3056
XS Rating Curve= 0 ,0
Exp/Cntr(USF)=0,0
Exp/Cntr=0.3,0.1

Type RM Length L Ch R = 1 ,20031   ,297.5,299.7,294.4
BEGIN DESCRIPTION:
Structure XS 4
END DESCRIPTION:
XS GIS Cut Line= 3
1677200.44142186398447.8149544471676707.22829735398779.625198302
1676620.01102192398856.043793697
#Sta/Elev= 30
       0  906.93      10  901.47    24.5  893.35      39  886.97    58.4  882.28
     142  882.42     227   874.2   323.8  874.99   352.4  873.44   381.1  874.72
   395.6   872.1     415  871.34   424.4  870.88   438.4  871.36   448.7  874.79
   463.2  876.98   479.2  886.19   496.5  900.17   502.2  903.06   531.6  904.54
   539.7  910.21   548.3   918.7   553.1   925.5   559.6   937.1   564.4  940.94
   585.8  951.09   617.1  969.81   630.5  973.72   662.5  986.15   710.4 1015.43
#Mann= 7 ,-1,0
       0    .025       0      10     .06       0     130      .1       0
     415    .045       0   438.4      .1       0     520     .06       0
  604.44      .1       0
Bank Sta=415,438.4
XS Rating Curve= 0 ,0
Exp/Cntr(USF)=0,0
Exp/Cntr=0.3,0.1

Type RM Length L Ch R = 1 ,19731   ,45.4,45.9,45.6
BEGIN DESCRIPTION:
Structure XS 3
END DESCRIPTION:
XS GIS Cut Line= 5
1677041.94481913398356.825698092 1676749.4261428398461.352371765
1676596.53638131398537.7972525121676498.25010606 398530.77680428
1676340.00164853398688.831111331
#Sta/Elev= 30
       0   888.7    44.4  887.03    65.7  885.69    78.4  883.85      92  883.36
   107.6  879.91   125.1   877.2   201.2  874.44   338.9  873.98   376.6  872.04
   398.3  869.52     406   868.6  413.22869.6383     415   870.4   421.3  875.39
   428.4  877.28     472  878.15     490   881.5   530.1  883.48   549.8  886.51
     597  886.83   602.7  889.27   628.1  907.61   645.3  918.37     651  920.83
   684.7  931.04   707.1   935.4   735.8  937.67   780.9  933.97   803.8  929.95
#Mann= 5 ,-1,0
       0      .1       0   398.3    .045       0  413.22      .1       0
  480.63     .06       0  590.11      .1       0
Bank Sta=398.3,413.22
XS Rating Curve= 0 ,0
Exp/Cntr(USF)=0,0
Exp/Cntr=0.3,0.1

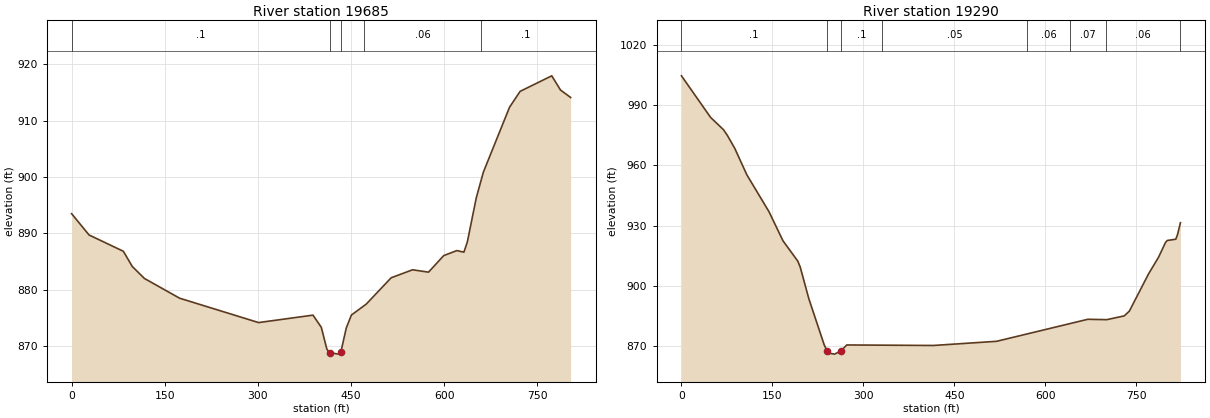
Type RM Length L Ch R = 1 ,19685   ,398.7,395.2,389.4
BEGIN DESCRIPTION:
Structure XS 2
END DESCRIPTION:
XS GIS Cut Line= 5
1677034.57084581398310.0118907171676742.05216948 398414.53856439
1676589.16240799398490.9834451361676490.87613275398483.962996904
1676332.62767521398642.017303956
#Sta/Elev= 30
       0  893.51    28.1  889.73    83.3  886.84    97.8  884.13   117.3  882.01
   173.9  878.51   301.2  874.18   388.8   875.5   402.2  873.34   411.2  869.45
  415.49868.8558   429.8  868.58   433.5  868.88   442.5  873.25   450.7  875.52
   474.6  877.46   514.7  882.13   549.2  883.55   574.9  883.13   599.4  886.07
   620.5  886.96   631.9  886.68   637.5  888.52   651.8  896.31   663.2  900.87
   705.4   912.4   722.4  915.22   773.4  917.98   787.5  915.46   803.8  914.14
#Mann= 5 ,-1,0
       0      .1       0  415.49    .045       0   433.5      .1       0
  470.63     .06       0  660.11      .1       0
Bank Sta=415.49,433.5
XS Rating Curve= 0 ,0
Exp/Cntr(USF)=0,0
Exp/Cntr=0.3,0.1

Type RM Length L Ch R = 1 ,19290   ,284.9,281.9,278.1
BEGIN DESCRIPTION:
Structure XS 1
END DESCRIPTION:
XS GIS Cut Line= 2
1676843.49930128397932.2185980311676210.96353737398458.193261327
#Sta/Elev= 30
       0 1004.43    48.1  983.74    69.3  977.64    75.6  974.86    88.1  968.24
   107.7  955.27   144.4  936.83   167.4  922.39   191.7  912.34   195.8  909.34
     210  893.59   235.5  870.53   239.8  867.82   243.7  866.46   252.6  866.05
   263.5867.8086   272.5  870.61   415.4  870.35   519.6  872.43   669.9  883.37
   701.2  883.19   729.8  885.05   738.3  887.38     770  905.92   786.6  914.27
   797.9  921.52   800.8  922.55     815   923.2   817.8   925.5   822.6  931.39
#Mann= 8 ,-1,0
       0      .1       0   239.8    .045       0   263.5      .1       0
     330     .05       0     570     .06       0     640     .07       0
     700     .06       0  822.65      .1       0
Bank Sta=239.8,263.5
XS Rating Curve= 0 ,0
Exp/Cntr(USF)=0,0
Exp/Cntr=0.3,0.1