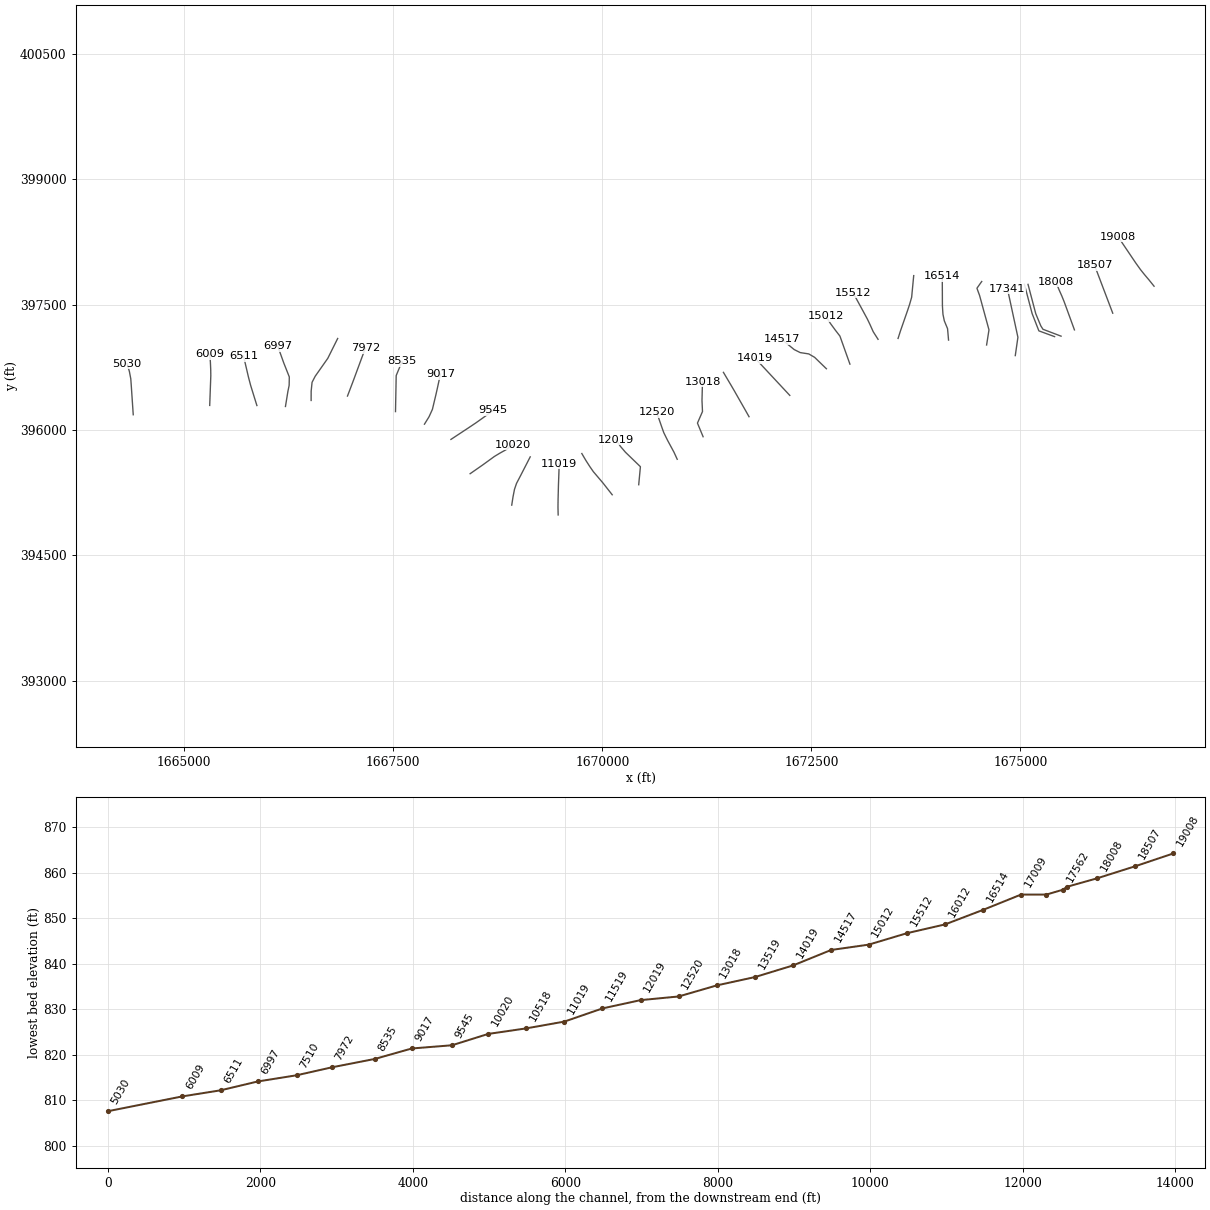
HEC-RAS study WILLEYFK.prj: WILLEYFK

--- WILLEYFK.g01 (geometry) --- (continued)

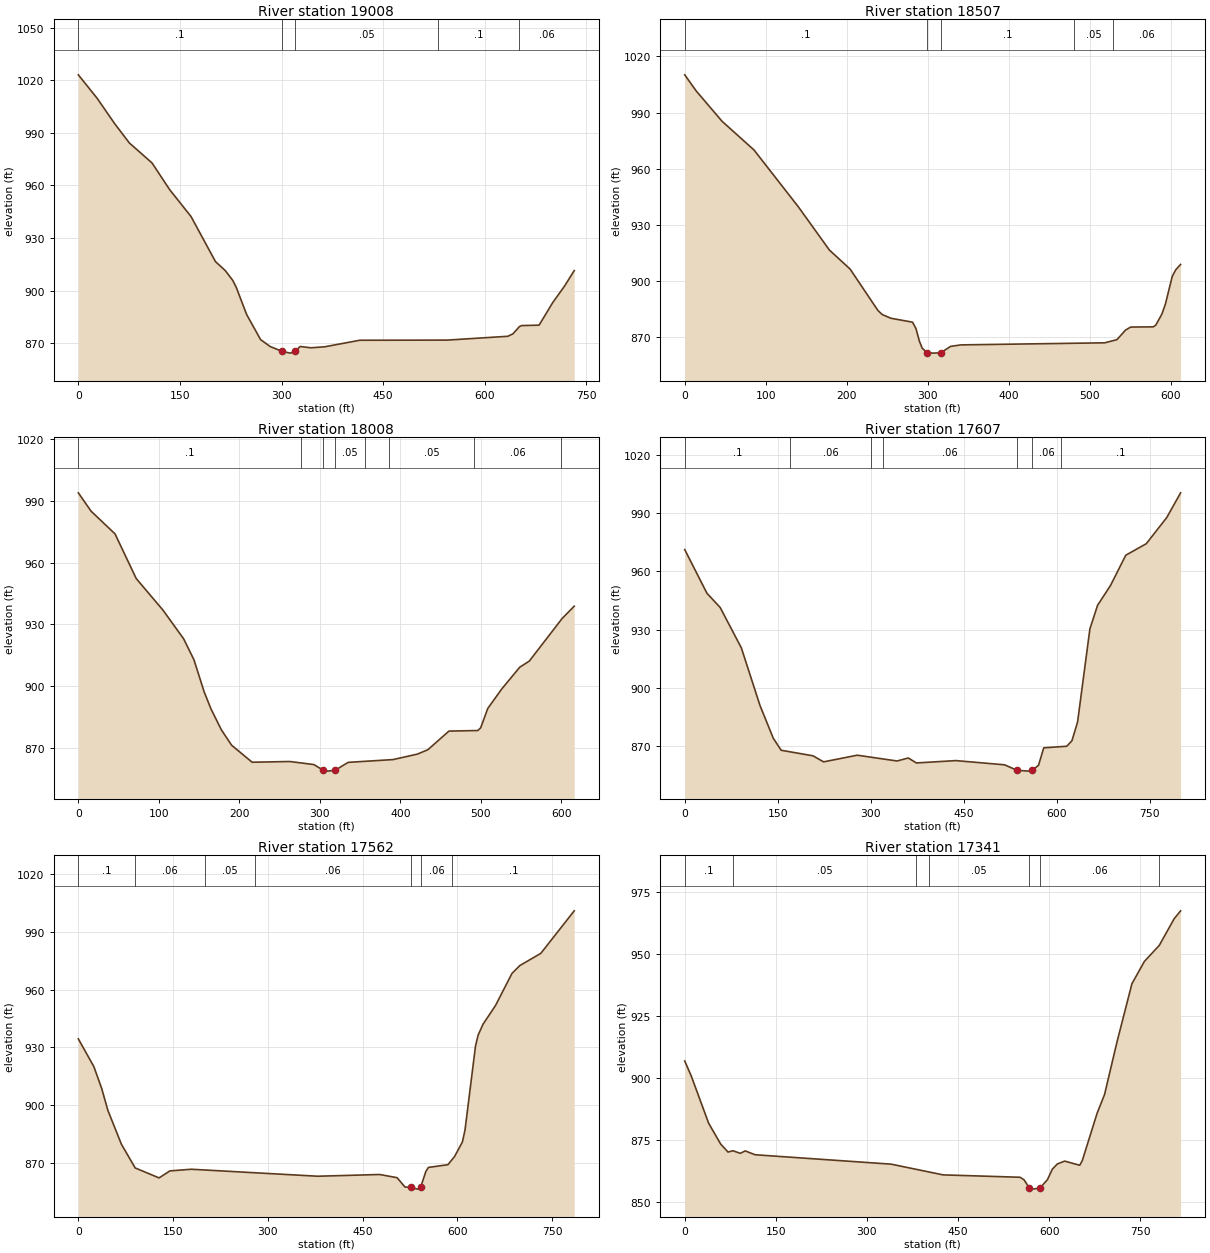
Type RM Length L Ch R = 1 ,19008   ,502.5,501.1,498
XS GIS Cut Line= 6
 1676597.6466725397720.0145693421676538.00834034 397794.09152092
1676481.16396584397861.5497193341676434.27954517397920.331097841
 1676376.1887821398001.7590845821676167.48311414398311.764158387
#Sta/Elev= 30
       0 1023.16      28 1009.66    53.5  995.36    75.4  984.24   108.8  972.87
   134.9  957.59   166.3  942.34   202.5  916.54   217.1  911.37   228.1  905.75
   233.2  901.82   248.5  886.36   269.1  872.02   283.3  868.06   300.4  865.37
   312.8  864.29   320.4  865.36   327.5  868.09   343.4  867.34   363.5  867.89
   415.6  871.64   544.9  871.73   634.3  873.91   641.8  875.34   651.4  879.47
   654.5  880.02   680.3  880.25   700.6  893.21   717.9  902.55   732.2  911.41
#Mann= 5 ,-1,0
       0      .1       0   300.4    .045       0   320.4     .05       0
  531.03      .1       0  651.03     .06       0
Bank Sta=300.4,320.4
XS Rating Curve= 0 ,0
Exp/Cntr(USF)=0,0
Exp/Cntr=0.3,0.1

Type RM Length L Ch R = 1 ,18507   ,499,499.2,498.8
XS GIS Cut Line= 6
 1676103.4196426397397.4719073331676070.17102142397485.128228083
1676039.13860318397566.9404004221675977.07442284397730.565073177
1675919.44330451397882.5021052511675886.19435526397970.158097923
#Sta/Elev= 30
       0 1010.16    14.2 1001.53    46.1  985.34    85.6  969.99   140.2  939.71
   178.7  916.54   204.3  906.36   238.6  884.27   243.8  882.12   254.6  880.11
   281.4  878.01   285.6  874.61   289.9  867.77   293.4  864.06   299.6  861.66
     307  861.47  316.18861.6501   328.4  865.07   341.2  865.87   518.8  866.98
   533.8  868.66   544.6  873.83   550.8   875.4   578.7  875.51   581.8  876.41
   589.4  882.36   593.7  887.69   602.2  902.53   606.5  906.01   612.5  908.86
#Mann= 5 ,-1,0
       0      .1       0   299.6    .045       0  316.18      .1       0
  481.25     .05       0  528.75     .06       0
Bank Sta=299.6,316.18
XS Rating Curve= 0 ,0
Exp/Cntr(USF)=0,0
Exp/Cntr=0.3,0.1

Type RM Length L Ch R = 1 ,18008   ,397.5,401,400.3
BEGIN DESCRIPTION:
Structure XS 4
END DESCRIPTION:
XS GIS Cut Line= 6
1675645.46386559 397197.699012921675583.30815001397367.958186835
1675523.29547475397532.3466375921675495.15543917397601.915068001
1675459.29330617397682.6901689171675424.62474035 397772.52955617
#Sta/Elev= 30
       0   993.8    15.8  984.92    45.6  973.88    71.9  952.23   105.2  936.88
   130.8  923.01   143.6  912.86   156.3  897.28   164.8  888.99   177.6  878.92
   190.4  871.39   215.9  863.14   262.8  863.48   292.6  862.01   304.1 859.283
   309.6  858.82  319.01859.2432   335.2  863.07     391  864.42   421.2  867.08
   434.2   869.2   460.4  878.24   496.2  878.51   499.8  879.82   508.6   889.2
   525.9  898.63   548.3  909.21   560.2  912.19   601.1   932.9     616  938.82
#Mann= 8 ,-1,0
       0      .1       0  276.25     .05       0   304.1    .045       0
  319.01     .05       0  356.25      .1       0  386.25     .05       0
  491.29     .06       0  599.67      .1       0
Bank Sta=304.1,319.01
XS Rating Curve= 0 ,0
Exp/Cntr(USF)=0,0
Exp/Cntr=0.3,0.1

Type RM Length L Ch R = 1 ,17607   ,46.2,44.4,42.9
BEGIN DESCRIPTION:
Structure XS 3
END DESCRIPTION:
XS GIS Cut Line= 5
1675485.56099847397122.5802655971675269.24216069397204.847315087
 1675243.4474154397245.8019414111675182.97479342397391.339141662
   1675090.50331397742.143658144
#Sta/Elev= 30
       0  971.25    35.8  948.75    57.2  941.37    91.4   920.5   121.4  890.85
   142.8  873.96   155.6   867.7     207  864.83   224.1  861.71   278.4  865.15
   342.6  862.16   360.8  863.71   373.8  861.15   437.5  862.36   516.1  860.19
   536.2  857.36   554.5  856.93  561.09857.3685     571  860.02   579.3  868.95
   616.5  869.77   624.8   872.6   633.9  882.23   653.8  930.34   666.2  942.51
   686.9  952.64   711.7  968.35   744.8  974.29   777.8  987.78   800.2 1000.55
#Mann= 7 ,-1,0
       0      .1       0     170     .06       0  299.83     .05       0
  319.83     .06       0   536.2    .045       0  561.09     .06       0
  607.44      .1       0
Bank Sta=536.2,561.09
XS Rating Curve= 0 ,0
Exp/Cntr(USF)=0,0
Exp/Cntr=0.3,0.1

Type RM Length L Ch R = 1 ,17562   ,221.3,221,220.7
BEGIN DESCRIPTION:
Structure XS 2
END DESCRIPTION:
XS GIS Cut Line= 4
1675408.08939535397116.9504605911675220.21082585397185.937122828
1675139.48175302397392.897109539 1675047.0102696397743.701626021
#Sta/Elev= 30
       0  934.49    24.6  920.05    37.1  908.57    46.8  897.28    68.2  879.69
      90  867.35   127.8  862.17   144.9   865.8   178.9  866.67     379  863.04
   477.1  863.94   504.7  862.28   517.1  857.45   526.2  857.19   537.7  856.33
   541.9  857.25   550.2  865.52   554.3  867.63   585.2  869.04   595.7  873.31
   608.1  880.87   612.2  887.08   628.8  930.67   632.9  936.39   640.8  942.16
   660.5  951.84   686.6  968.56   699.1  972.64   732.2  978.96   785.1 1001.09
#Mann= 7 ,-1,0
       0      .1       0      90     .06       0     200     .05       0
  280.14     .06       0   526.2    .045       0   541.9     .06       0
  592.29      .1       0
Bank Sta=526.2,541.9
XS Rating Curve= 0 ,0
Exp/Cntr(USF)=0,0
Exp/Cntr=0.3,0.1

Type RM Length L Ch R = 1 ,17341   ,331.2,332.2,333.2
BEGIN DESCRIPTION:
Structure XS 1
END DESCRIPTION:
XS GIS Cut Line= 3
1674938.12652573396889.9581513871674969.44677956397109.199928206
1674844.16576424397690.861785073
#Sta/Elev= 30
       0  906.87    10.7  900.87    39.4  881.79    59.2   873.4    71.3  870.19
    79.4  870.71    91.5  869.66    99.6  870.65   115.7   869.1   339.9   865.3
   425.4  860.98   552.2  860.02   558.7     859  567.56855.6823   572.7  855.24
     585  855.69   597.2  859.06   605.4  863.32   613.6   865.4   625.6  866.53
   650.4  864.86   654.5  866.68   679.1  885.89   691.3  893.41   711.8  914.62
   736.3  938.01   756.8  946.99   781.4  953.49   805.9  964.22   816.5   967.4
#Mann= 7 ,-1,0
       0      .1       0      80     .05       0  381.47      .1       0
  401.47     .05       0  567.56    .045       0     585     .06       0
  781.47      .1       0
Bank Sta=567.56,585
XS Rating Curve= 0 ,0
Exp/Cntr(USF)=0,0
Exp/Cntr=0.3,0.1

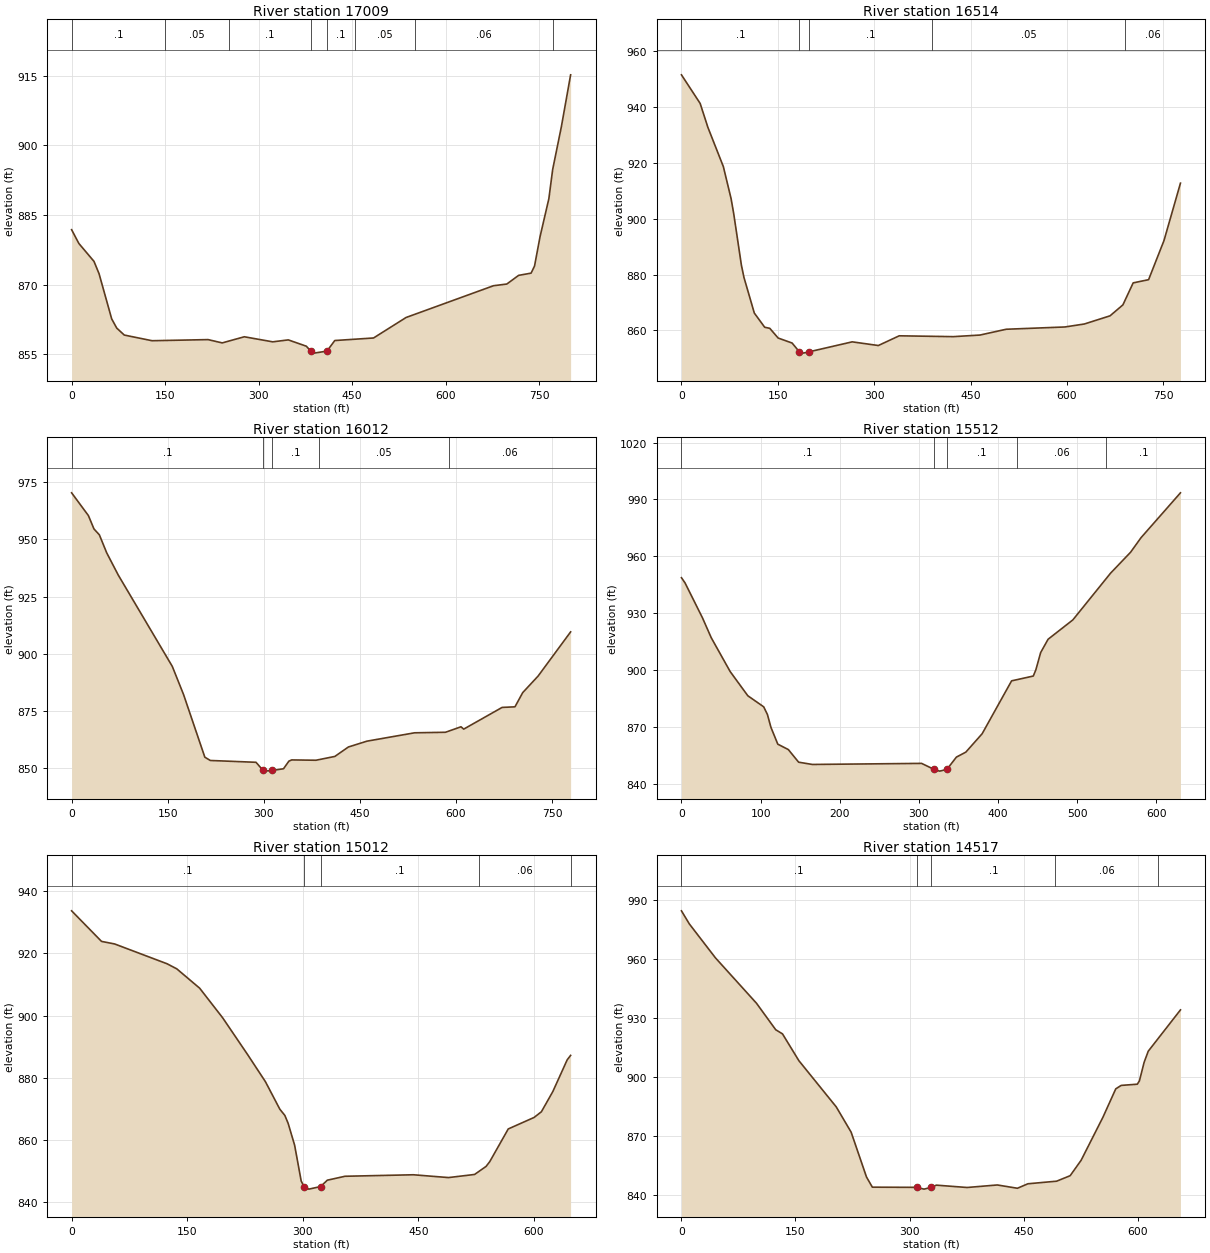
Type RM Length L Ch R = 1 ,17009   ,493.5,494.8,495
XS GIS Cut Line= 6
1674595.10925097 397017.033613881674623.58894084397197.599603668
1674600.56667717397282.0164295881674511.76304901397607.623718008
1674479.64541012 397695.939243321674536.77661117397776.635948798
#Sta/Elev= 30
       0  881.81    11.6  878.85    35.9  874.99      44  872.35    64.3  862.61
    72.4  860.63    84.5  859.13   129.1  857.91     219  858.15   241.6  857.44
   277.1  858.76   322.7  857.67   347.6  858.09   376.6  856.73  383.61855.6873
     389  855.24   409.7  855.68   422.2  857.95   484.4   858.5   536.6  862.91
   676.9  869.75   698.2  870.11   717.2  871.98   737.2  872.46   742.7  873.99
   751.5  880.28   765.7  888.49   771.8  894.77   785.8  904.01   800.6  915.15
#Mann= 8 ,-1,0
       0      .1       0     150     .05       0   252.8      .1       0
  383.61    .045       0   409.7      .1       0   455.3     .05       0
   550.3     .06       0  771.77      .1       0
Bank Sta=383.61,409.7
XS Rating Curve= 0 ,0
Exp/Cntr(USF)=0,0
Exp/Cntr=0.3,0.1

Type RM Length L Ch R = 1 ,16514   ,506.7,502.5,496.4
XS GIS Cut Line= 6
1674140.12068329397075.5580356631674128.28022018397211.878446504
 1674089.3997205397306.1508957591674073.12941185397386.078885511
1674066.80134051397485.9507330061674065.09405572  397842.1453782
#Sta/Elev= 30
       0  951.37    29.1  941.15    41.1  932.62    65.2  918.57    77.3  907.06
    81.3  901.79    93.3  883.33    97.3  878.93   113.4  866.22   129.5  861.16
   137.5  860.76   150.5  857.29   172.2  855.51  183.69852.3088   189.5   851.9
   198.1  852.34   265.7  855.93   306.4  854.62   338.9  858.09     423  857.79
   464.6  858.36   505.3  860.43   596.9  861.25     627  862.31     667  865.23
     687  869.14     703  877.01     727  878.15     751  892.16   776.6  912.65
#Mann= 5 ,-1,0
       0      .1       0  183.69    .045       0   198.1      .1       0
  390.38     .05       0  690.45     .06       0
Bank Sta=183.69,198.1
XS Rating Curve= 0 ,0
Exp/Cntr(USF)=0,0
Exp/Cntr=0.3,0.1

Type RM Length L Ch R = 1 ,16012   ,494.8,500.2,507.2
XS GIS Cut Line= 6
1673536.53337218397095.2654907551673564.89584826397184.659997001
1673651.20538692397432.5643568341673674.70763651397503.797810167
1673698.94708934397588.0102401671673723.57794559397846.975586705
#Sta/Elev= 30
       0  970.39    26.2  960.45    34.9   954.6    43.3  952.03    54.8  944.14
    72.7  934.49   157.2  894.48   174.8  882.16     208  854.78   216.5  853.34
   287.9  852.54  299.03848.9631   301.2  848.68     313  848.97   330.8  849.71
   339.3  853.06   343.6  853.58   381.5  853.44     411  855.11   432.1  859.23
   461.2  861.79   535.5  865.44   583.7  865.67   607.9  868.07   612.2  867.05
   672.1  876.54   692.2   876.8   704.3  883.01   728.4  890.28   779.1  909.57
#Mann= 5 ,-1,0
       0      .1       0  299.03    .045       0     313      .1       0
  386.29     .05       0  588.93     .06       0
Bank Sta=299.03,313
XS Rating Curve= 0 ,0
Exp/Cntr(USF)=0,0
Exp/Cntr=0.3,0.1

Type RM Length L Ch R = 1 ,15512   ,499.4,499.8,488.7
XS GIS Cut Line= 6
1673297.14310293397084.8573750851673239.43554117 397175.48153767
1673202.16494642397258.8353735951673169.63384351397326.750592083
1673122.16379409   397414.765836  1672999.805443397639.915648177
#Sta/Elev= 30
       0  948.75     4.4   946.1    26.6  927.54    37.6  917.11    61.5  899.28
    83.8  886.51   103.9  880.65   108.6   876.6     113  869.88   121.7  860.96
     135  858.12     148  851.46   165.3  850.27   303.3  850.83  319.15847.6581
   326.1  846.75   335.2  847.62   347.3  854.15   359.2  856.77   379.8  866.46
     417  894.36   444.4  896.89   447.7  900.23   453.7  909.26   463.1  916.29
   494.4  926.51     542  951.13   567.3  962.18   580.4  969.81   630.3  993.51
#Mann= 5 ,-1,0
       0      .1       0  319.15    .045       0   335.2      .1       0
  424.05     .06       0  536.55      .1       0
Bank Sta=319.15,335.2
XS Rating Curve= 0 ,0
Exp/Cntr(USF)=0,0
Exp/Cntr=0.3,0.1

Type RM Length L Ch R = 1 ,15012   ,480.8,494.4,501.1
XS GIS Cut Line= 6
1672960.83209576   396787.9481921672874.77058809397029.295478344
1672841.24736117397123.5088725841672790.44168851397189.016943678
1672730.42474817397270.8504414261672671.73949809 397360.22296609
#Sta/Elev= 30
       0  933.63    38.8  923.81    55.8  922.99   123.8  916.63   136.5  914.99
   166.2  908.77     196  899.27   228.4  887.45   251.5  878.75   270.2  869.91
   276.7  867.91   280.9  865.43   289.4  858.34   297.9  846.85   301.6  845.01
   307.8  844.24   323.1  845.06   331.8  847.11   354.8  848.37   443.5  848.85
   489.1  847.95   522.9  848.95   537.8  851.53   542.6  853.07   566.6  863.57
   600.1  867.26   609.6  869.09   624.4  875.56   643.1  885.78   647.5   887.2
#Mann= 5 ,-1,0
       0      .1       0   301.6    .045       0   323.1      .1       0
  529.13     .06       0  647.53      .1       0
Bank Sta=301.6,323.1
XS Rating Curve= 0 ,0
Exp/Cntr(USF)=0,0
Exp/Cntr=0.3,0.1

Type RM Length L Ch R = 1 ,14517   ,505,497.9,494
XS GIS Cut Line= 6
1672679.43338034396732.695021674 1672538.2417336396869.519551173
1672468.23892084396910.1605460051672366.92974025396925.766814008
1672294.53355959396961.8992876711672144.43576267397085.102453336
#Sta/Elev= 30
       0  984.29    10.3  977.68    44.8  960.38    98.7  937.39     124  923.94
   132.9  921.85   154.5  908.22   203.6   884.8   223.2  871.97   243.4  849.22
   251.1  844.05   309.3  843.96   319.1  843.06   328.5  843.95   335.3  845.07
   375.8  843.89   415.5  845.17   441.9   843.5   455.7  845.77   493.5  847.09
   511.3  849.88   525.7  857.68   554.4  879.53   571.3  893.95   578.4  895.69
   599.6  896.31   602.4  897.99   608.6  907.41     614  913.03   656.4  934.02
#Mann= 5 ,-1,0
       0      .1       0   309.3    .045       0   328.5      .1       0
  491.94     .06       0  626.25      .1       0
Bank Sta=309.3,328.5
XS Rating Curve= 0 ,0
Exp/Cntr(USF)=0,0
Exp/Cntr=0.3,0.1

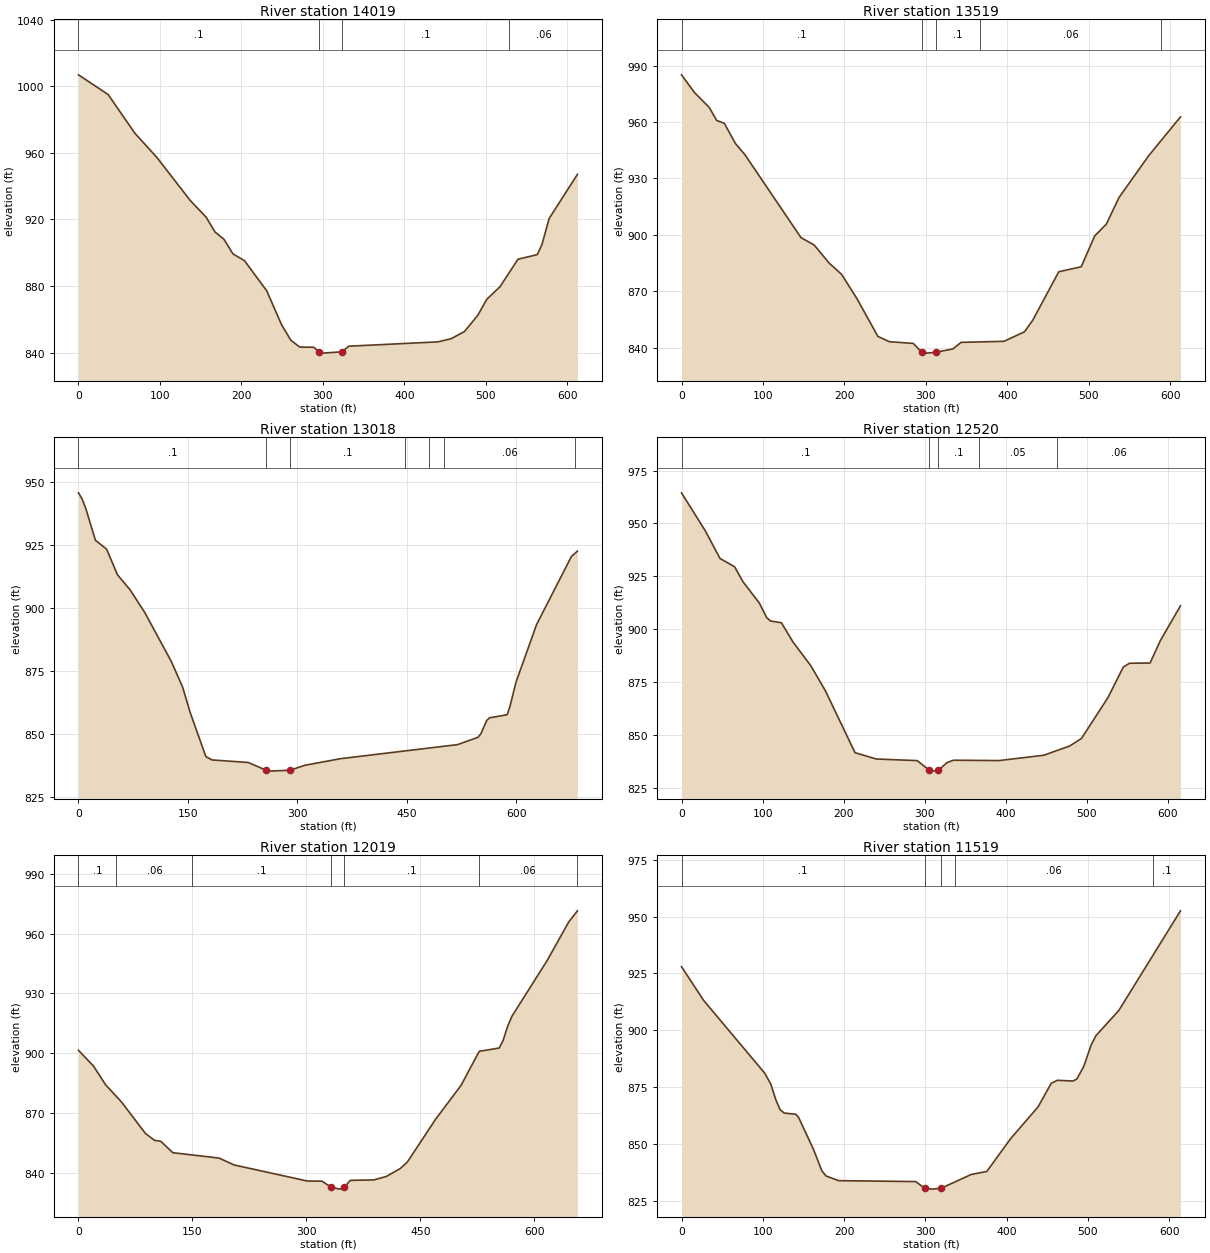
Type RM Length L Ch R = 1 ,14019   ,501.8,500,494
XS GIS Cut Line= 6
1672241.67146058 396413.911866591672177.74573542396482.486860678
1672118.08148468396546.490341589 1671947.6126655396729.357429922
1671887.94841476396793.3609108331671824.02301767396861.936561093
#Sta/Elev= 30
       0 1006.89    36.4  995.06    69.2  971.82    96.4  957.16   137.2  931.38
   156.7  921.37   167.6  912.43   178.6  908.08   189.5  899.34   203.9  895.17
   231.1  877.08   249.2  856.84   260.6  847.48   271.5  843.32   288.8   843.2
   295.6  840.41   300.1  839.67   323.3840.4485   331.7  843.83   441.1  846.43
   457.5  848.34   473.9  852.68   490.3   862.5   501.2     872   517.6  879.67
   539.5  896.08   563.3  898.88     569  905.03   577.8  920.59   612.5  947.09
#Mann= 4 ,-1,0
       0      .1       0   295.6    .045       0   323.3      .1       0
  528.75     .06       0
Bank Sta=295.6,323.3
XS Rating Curve= 0 ,0
Exp/Cntr(USF)=0,0
Exp/Cntr=0.3,0.1

Type RM Length L Ch R = 1 ,13519   ,514.5,501.2,488.2
XS GIS Cut Line= 6
  1671754.319745396158.8654606791671708.21714692396240.491937846
1671578.40900759396468.6502741721671540.58690476 396533.42015776
1671495.98889685396608.7172512561671448.26884793396689.444123924
#Sta/Elev= 30
       0  985.11    15.7   975.8    34.1  967.72    43.3  960.79    52.5  959.36
    66.2  948.56    77.7  942.72   146.7  898.52   162.8  894.64   181.2  885.01
   196.5     879   215.3  866.13   241.1  845.99   255.2  843.19   284.5  842.28
  294.89837.6104   300.9  837.11   312.4  837.56   333.1  839.35   343.2  842.84
   395.9  843.39     421  848.46     431  854.49   463.1  880.38   490.7  883.05
   507.2  899.43   521.5  905.71   537.1  919.89   573.5  942.11   612.5  962.73
#Mann= 5 ,-1,0
       0      .1       0  294.89    .045       0   312.4      .1       0
  366.25     .06       0  588.76      .1       0
Bank Sta=294.89,312.4
XS Rating Curve= 0 ,0
Exp/Cntr(USF)=0,0
Exp/Cntr=0.3,0.1

Type RM Length L Ch R = 1 ,13018   ,483.5,498.3,509.5
BEGIN DESCRIPTION:
Low water crossing
END DESCRIPTION:
XS GIS Cut Line= 5
1671205.16752979 395919.211316521671137.64866888396082.137263506
1671197.82852317 396220.110587981671191.95731788396353.680508482
1671197.82852317396576.786309759
#Sta/Elev= 30
       0  945.73     4.9  943.35    10.1  939.43    23.2  926.91    38.6  923.35
    53.4  913.22    70.7  907.23    90.6  898.36   127.3  878.74   142.6  868.72
     153   858.6   174.6  841.03   183.3  839.71   232.6  838.72   257.5  835.59
   261.9  835.28  290.13835.6395   309.9  837.58   359.3  840.23   519.5   845.8
   547.5   848.7   551.5  850.14   559.5   855.4   563.5  856.45   587.5  857.66
   591.5  861.12   599.5  870.48   627.7  893.38   675.5  920.45   683.8  922.59
#Mann= 7 ,-1,0
       0      .1       0   257.5    .045       0  290.13      .1       0
  446.89     .05       0  480.59     .07       0  500.59     .06       0
  680.59      .1       0
Bank Sta=257.5,290.13
XS Rating Curve= 0 ,0
Exp/Cntr(USF)=0,0
Exp/Cntr=0.3,0.1

Type RM Length L Ch R = 1 ,12520   ,498.2,501.1,503.1
XS GIS Cut Line= 6
 1670895.7804516395649.3710728441670856.56694734395734.686519012
1670779.39387333395877.6980440021670735.00288601395967.845829591
1670709.44847517396039.3325632511670649.98533951396211.926050082
#Sta/Elev= 30
       0  964.46    29.3  946.52    47.5  933.41    65.5  929.49    75.8  922.42
      96  912.33     105  905.49   109.6  903.86   123.2  903.03   137.5  893.93
   159.4  882.74   177.5  870.84     214  841.57   240.3  838.58   290.8  837.82
   305.8   833.2   308.8  832.85   316.9  833.23   327.2  836.84   335.4  838.01
   391.6  837.84   446.8  840.36   478.8  844.74   493.3  848.31     526  867.65
   544.9  882.05   552.6  883.87   577.9  883.97   590.6  894.58   615.4  911.04
#Mann= 5 ,-1,0
       0      .1       0   305.8    .045       0   316.9      .1       0
  366.89     .05       0  462.81     .06       0
Bank Sta=305.8,316.9
XS Rating Curve= 0 ,0
Exp/Cntr(USF)=0,0
Exp/Cntr=0.3,0.1

Type RM Length L Ch R = 1 ,12019   ,500.3,499.6,499.4
XS GIS Cut Line= 6
1670435.32922297395344.8455804531670455.59301175395560.594347507
1670329.76977259395682.2230412511670275.79054984395734.514275253
1670217.13285875 395803.39241834  1670161.732379395885.662266925
#Sta/Elev= 30
       0  901.55    19.8  893.64    35.8  884.22    56.4  875.78    88.1  859.91
   100.1  856.46   108.2  856.01   124.2  850.27     185  847.59   204.6  844.16
   301.2  836.09   320.2  836.03   332.8  832.98   343.6  832.04  349.95833.0472
   357.7  836.44   388.8  836.64   405.1  838.39   423.8  842.46     433  845.76
   469.5  866.82   503.4  884.01   527.3  901.05   553.6  902.69   558.9  906.68
   564.6  913.51   570.4  918.66   616.6  946.46   645.1  965.84   656.5  971.39
#Mann= 7 ,-1,0
       0      .1       0      50     .06       0     150      .1       0
   332.8    .045       0  349.95      .1       0  526.85     .06       0
  656.51      .1       0
Bank Sta=332.8,349.95
XS Rating Curve= 0 ,0
Exp/Cntr(USF)=0,0
Exp/Cntr=0.3,0.1

Type RM Length L Ch R = 1 ,11519   ,505.4,500.7,492.3
XS GIS Cut Line= 6
1670118.40667826395224.690163672 1670006.4653011395367.424130172
1669893.04098725395500.7975510951669850.23759517395562.585157171
1669802.71866134395636.5597467571669755.12951767395717.996919841
#Sta/Elev= 30
       0  927.95    27.2  913.16   102.4  881.16   109.9  876.34     116  869.52
   121.3  865.12   126.3  863.65   140.6  863.13   144.1   861.7   162.3  847.76
   172.6  838.33   177.7  836.02   193.4  833.94     288  833.54  299.37830.5884
   308.4  830.22   319.4   830.6   356.5  836.66   375.6  837.97   404.8  852.34
   438.7  866.36   454.9  876.72   462.5  878.04   481.5  877.72   486.3  878.56
   494.8  884.03   504.1  893.64   509.9  897.66   538.1  908.74   613.9   952.5
#Mann= 5 ,-1,0
       0      .1       0  299.37    .045       0   319.4      .1       0
  336.46     .06       0  579.58      .1       0
Bank Sta=299.37,319.4
XS Rating Curve= 0 ,0
Exp/Cntr(USF)=0,0
Exp/Cntr=0.3,0.1

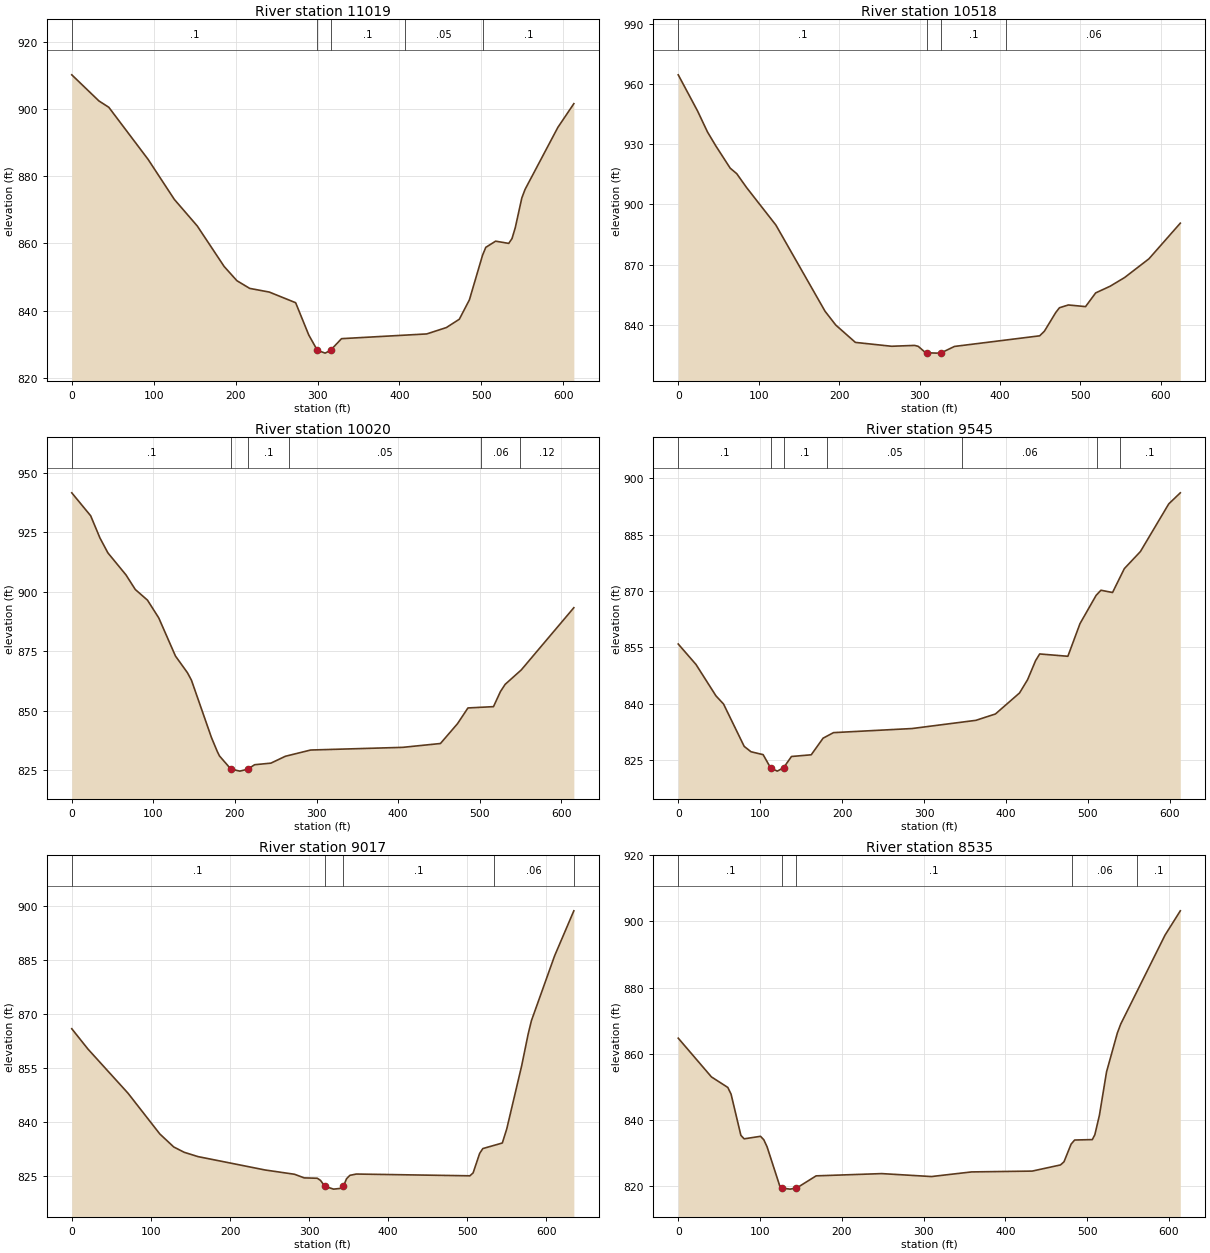
Type RM Length L Ch R = 1 ,11019   ,503.4,500.1,495.6
XS GIS Cut Line= 6
1669472.08874518394983.3619061711669470.00180709395077.421101257
1669471.04642442395165.0190231651669475.50015567395339.975038096
1669481.53557667395502.340527013 1669484.0431176395596.065405175
#Sta/Elev= 30
       0  910.25    33.2  902.46    45.2  900.58    93.2  885.05   125.2  873.13
   153.2  865.21   186.1  853.11   201.6   848.9   217.2  846.61   241.2  845.51
   273.3  842.34   289.3  832.73  299.73828.1898   309.3  827.32   315.9  828.17
   329.3  831.63   433.3  833.04   457.3  834.94   473.1  837.42   485.4   843.2
   501.4  856.46   505.4  858.84   517.4  860.68   533.4  860.02   537.4  861.45
   541.4   864.7   549.4  873.57   553.4  876.13   593.4  894.59   612.9  901.65
#Mann= 5 ,-1,0
       0      .1       0  299.73    .045       0   315.9      .1       0
   406.7     .05       0   501.7      .1       0
Bank Sta=299.73,315.9
XS Rating Curve= 0 ,0
Exp/Cntr(USF)=0,0
Exp/Cntr=0.3,0.1

Type RM Length L Ch R = 1 ,10518   ,502,498.6,492.3
XS GIS Cut Line= 6
1668916.96452734395100.7120651751668932.20038925395198.608194843
1668949.71872692395289.0706123411668974.39551485395361.402488679
1669020.86261351395450.1893845951669137.92274684395678.138731837
#Sta/Elev= 30
       0  964.58    24.1   946.5    36.3  936.14    46.5  929.29    64.6  918.04
    72.7  915.31    84.8  908.46   121.4  889.67   182.5  846.71   195.8  839.83
   220.2  831.18   265.2  829.25   293.8  829.68   298.3  829.22   306.8  826.27
   309.8     826   321.6  825.83  326.93825.9966   343.4  829.17   449.3  834.46
   455.2  836.79   469.4  846.16   473.9  848.46   484.9  849.84   506.3  849.02
   518.9  855.86   536.9  859.19   554.9  863.53   585.1  872.85   624.1  890.62
#Mann= 4 ,-1,0
       0      .1       0   309.8    .045       0  326.93      .1       0
  407.85     .06       0
Bank Sta=309.8,326.93
XS Rating Curve= 0 ,0
Exp/Cntr(USF)=0,0
Exp/Cntr=0.3,0.1

Type RM Length L Ch R = 1 ,10020   ,473.5,474.4,472.5
XS GIS Cut Line= 6
 1668419.5897623395476.8119589261668568.37522588395580.492525848
1668710.00945705395683.3049842591668774.44896072395722.267832847
1668851.15550021395765.105345594 1668927.6064628395823.016647102
#Sta/Elev= 30
       0  941.57    23.2  931.91    34.6  922.55    44.3  916.33    66.4   907.1
    77.9  900.93    92.8  896.47   106.6  889.02   127.1  872.98   141.8  865.96
   146.7  862.82   171.2  838.74   178.3  832.91     181  831.01     195825.4849
     206  824.61   215.5   825.4   224.1   827.3   244.1  827.97   261.8  830.85
   292.8  833.48   405.6   834.6   451.9  836.22   472.8  844.55   485.6  851.16
   516.9  851.71   525.5  858.09   531.2  861.08   550.9  867.12   615.4  893.29
#Mann= 6 ,-1,0
       0      .1       0     195    .045       0   215.5      .1       0
  266.35     .05       0  501.68     .06       0  549.54     .12       0
Bank Sta=195,215.5
XS Rating Curve= 0 ,0
Exp/Cntr(USF)=0,0
Exp/Cntr=0.3,0.1

Type RM Length L Ch R = 1 ,9545    ,516,528.5,533.9
XS GIS Cut Line= 6
1668189.99463531395887.1260711221668403.86264589396028.280972552
1668486.94450072396083.9393257911668548.18059873396127.312270548
1668619.35893405396178.3138089591668695.50838806396233.129644211
#Sta/Elev= 30
       0   855.9    21.7  850.46    46.1  842.11    55.3  839.95    80.5  828.69
    88.8  827.27   103.6   826.5   112.8  822.96   120.9  822.12   128.5823.0088
   138.2  826.01   162.3  826.46   176.8  830.88   189.5  832.35   285.4  833.44
   363.3  835.62   387.1  837.31   416.5  842.89   426.3  846.41   436.1  851.49
   441.1  853.26   475.5  852.64   490.3  861.33   509.9  868.81   515.8  870.19
     530  869.59   544.4  875.94     564  880.47   598.6  893.14   612.7  896.08
#Mann= 7 ,-1,0
       0      .1       0   112.8    .045       0   128.5      .1       0
  181.25     .05       0  346.25     .06       0  511.29     .07       0
  538.86      .1       0
Bank Sta=112.8,128.5
XS Rating Curve= 0 ,0
Exp/Cntr(USF)=0,0
Exp/Cntr=0.3,0.1

Type RM Length L Ch R = 1 ,9017    ,477.5,481.9,483.1
XS GIS Cut Line= 6
1667873.39738876396069.4335529211667928.52523126396158.797875509
1667968.41261867396246.5349047481668009.46896701396418.614613086
1668026.03192601 396491.773587511668064.57023476396668.909388095
#Sta/Elev= 30
       0  865.96    20.4  860.33    71.1  848.05   111.3  836.73   128.9  833.12
   142.1  831.64   159.6  830.44   244.5  826.72   281.5  825.54   293.8  824.53
   310.3  824.43   314.4  823.84  319.72  822.22   330.9  821.41   339.1   821.6
   343.2  822.17   347.3  824.29   351.5  825.24   359.7   825.6   503.2  825.11
   507.3  825.92   515.5  831.31   519.6  832.68   544.2  834.22   549.8  838.14
   568.7  855.72   576.9  864.53     581  868.21   610.3  886.22   634.6  898.71
#Mann= 5 ,-1,0
       0      .1       0  319.72    .045       0   343.2      .1       0
   533.3     .06       0  634.58      .1       0
Bank Sta=319.72,343.2
XS Rating Curve= 0 ,0
Exp/Cntr(USF)=0,0
Exp/Cntr=0.3,0.1

Type RM Length L Ch R = 1 ,8535    ,565.6,562.9,559.9
XS GIS Cut Line= 6
 1667527.0939197396219.9756954981667528.90493971396313.708447672
1667530.59489695396401.1921965851667533.97546762396576.159366332
1667535.42493979396651.1454368311667605.35941264396819.883311083
#Sta/Elev= 30
       0  864.74    40.6  853.03    60.6  849.85    64.6  847.83    76.6  835.37
    80.6  834.32   100.6  835.08   104.6  834.05   108.6  831.93   124.6  819.73
  127.41819.4139   136.6  819.12   144.6  819.42   168.6  823.13   248.8  823.81
   309.6  822.92   358.7  824.32   432.8  824.57   467.4  826.43   471.7  827.39
   480.4  832.73   484.7  833.96   506.3  834.09   509.4  835.56     515  841.45
   523.7  854.55   536.9  866.28     541  868.98   595.2  895.87   613.9  903.22
#Mann= 5 ,-1,0
       0      .1       0  127.41    .045       0   144.6      .1       0
  481.25     .06       0  561.25      .1       0
Bank Sta=127.41,144.6
XS Rating Curve= 0 ,0
Exp/Cntr(USF)=0,0
Exp/Cntr=0.3,0.1

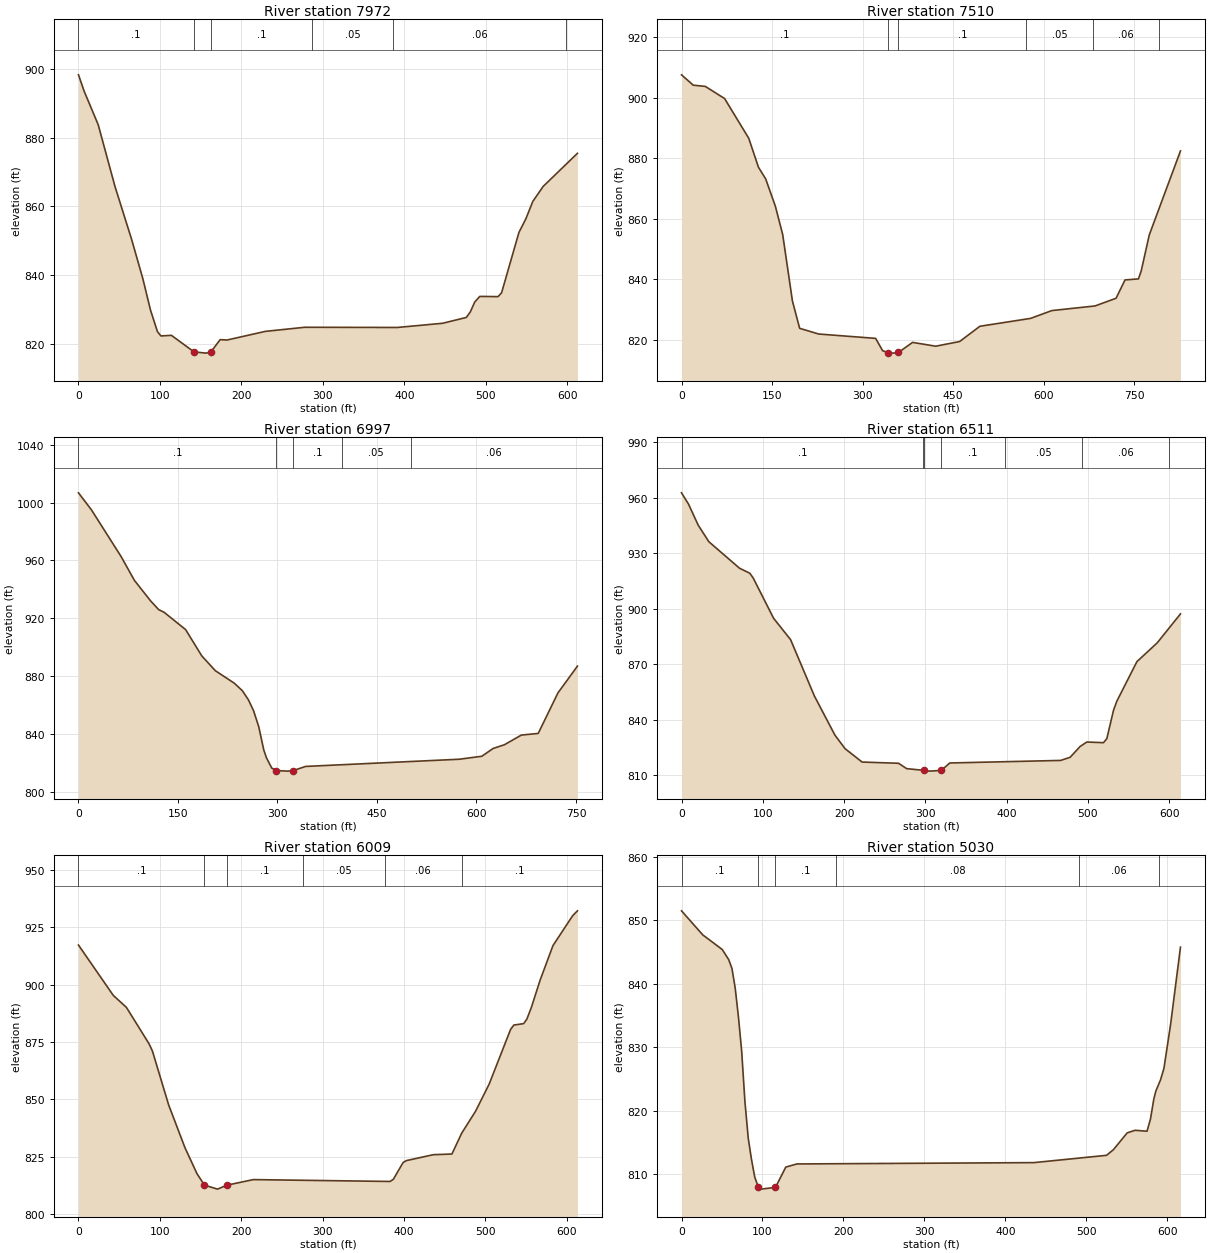
Type RM Length L Ch R = 1 ,7972    ,461.8,462.5,458.1
XS GIS Cut Line= 6
1666952.93037745396405.9520295781666986.33319779396493.555200838
1667017.30426445396575.393619828 1667043.4134642396645.702862419
1667104.01308054396809.8754343321667166.77804687396979.911183499
#Sta/Elev= 30
       0  898.26       7  893.47    24.2  883.75    44.8  865.78    65.1  850.47
    78.9  839.04    88.4  829.81    96.9  823.55   101.2  822.28   114.1  822.45
  141.81817.6413   156.8  817.28   162.6  817.64   173.9   821.2   182.5   821.1
   229.4  823.61   277.7   824.8   391.5  824.75   446.9  825.96   476.1  827.66
     481  829.28   486.4  832.13   492.6  833.78   515.1  833.72   519.4  834.85
   540.7  852.41   549.2  856.36   557.7  861.42   570.5  865.81   612.5  875.42
#Mann= 6 ,-1,0
       0      .1       0  141.81    .045       0   162.6      .1       0
  286.26     .05       0  386.26     .06       0  598.76      .1       0
Bank Sta=141.81,162.6
XS Rating Curve= 0 ,0
Exp/Cntr(USF)=0,0
Exp/Cntr=0.3,0.1

Type RM Length L Ch R = 1 ,7510    ,505.2,512.4,508
XS GIS Cut Line= 6
1666518.23408858 396353.150505171666518.54642393396464.397001833
1666529.45519476 396570.283601091666566.46824409396642.261475503
1666717.42201042396857.1951007551666835.64808368397094.805636223
#Sta/Elev= 30
       0  907.57    19.4  904.15    39.4  903.74    71.4  899.72   111.4   886.6
   127.5  877.02   139.5  873.14   155.6  864.08   167.7  854.73   183.8   832.8
   195.8  823.73   227.3  821.85   321.7  820.41   333.2  816.35   341.9  815.71
   350.5  815.53   359.5  815.74   382.9  819.08   421.3  817.82   460.9  819.36
   494.5  824.41   578.6  827.02   613.7   829.6   685.3  831.13   720.2  833.68
     735  839.74   757.3  840.08   761.8  842.69   775.2  854.61   826.9   882.4
#Mann= 6 ,-1,0
       0      .1       0   341.9    .045       0   359.5      .1       0
  571.47     .05       0  681.47     .06       0  791.47      .1       0
Bank Sta=341.9,359.5
XS Rating Curve= 0 ,0
Exp/Cntr(USF)=0,0
Exp/Cntr=0.3,0.1

Type RM Length L Ch R = 1 ,6997    ,483.5,486.3,488.8
XS GIS Cut Line= 6
1666211.31016175396281.0797831711666240.33142917396460.431458592
1666255.40620217396534.0776367491666257.28283884396634.244431168
1666190.59137118396803.1771641671666118.63650809397004.204527936
#Sta/Elev= 30
       0 1006.74    19.7  994.85    64.2  962.68    84.4   946.1   108.7  931.98
   120.9  925.91     129  924.11   161.5   912.1   185.9  893.89   206.3  883.67
   234.9     875   247.1  869.78   256.2  863.49   263.9  856.02   271.8  844.84
   279.3  828.87   283.3  823.47   291.3  816.31  297.99814.5836   315.3  814.16
  323.66814.5261   342.4  817.41   574.1  822.39   608.1  824.45   625.1  829.85
   642.1  832.42   667.6  839.09   693.1  840.26   722.8  868.28   752.2  886.82
#Mann= 5 ,-1,0
       0      .1       0  297.99    .045       0  323.66      .1       0
  397.05     .05       0  500.59     .06       0
Bank Sta=297.99,323.66
XS Rating Curve= 0 ,0
Exp/Cntr(USF)=0,0
Exp/Cntr=0.3,0.1

Type RM Length L Ch R = 1 ,6511    ,504.5,502.4,495.9
XS GIS Cut Line= 6
1665869.73276092396292.3412435951665841.71838126396382.234436512
1665815.74533609396466.3579559181665793.50981626396538.456893086
1665768.19687475396635.3366205841665709.90729317396884.745242506
#Sta/Elev= 30
       0  962.53     8.6  956.45    20.6  945.01    33.7   936.1    71.4   921.8
      84  919.11    88.2  916.53   113.3  894.78   134.2  883.24   163.5  852.79
   188.7  831.71   201.2  824.36   222.2  817.12   267.1  816.46   276.9  813.58
  298.81812.5904   305.3  812.22   319.5  812.59   330.1  816.62   466.5     818
   478.1  819.68   490.5  825.56   498.7  827.94   519.2  827.59   523.3  829.76
   531.5  845.04   535.6  849.99   560.3  871.34   585.3  881.51   613.9  897.14
#Mann= 7 ,-1,0
       0      .1       0  297.65     .05       0  298.81    .045       0
   319.5      .1       0  397.78     .05       0  492.75     .06       0
  600.21      .1       0
Bank Sta=298.81,319.5
XS Rating Curve= 0 ,0
Exp/Cntr(USF)=0,0
Exp/Cntr=0.3,0.1

Type RM Length L Ch R = 1 ,6009    ,976.1,978.2,979.8
XS GIS Cut Line= 6
1665305.55081337396293.7259089411665308.99437604396387.412729433
1665318.63936987396649.7353675281665317.46581579396724.829377434
1665313.60886811396812.5299894421665306.12659962396906.537675446
#Sta/Elev= 30
       0  917.26    42.8  895.32    58.9  890.12    86.9  874.15    90.9  871.07
   110.9  847.53   130.9  828.95   145.7   817.6   154.9  812.62   170.9  810.88
   182.8  812.63     215  815.03   383.1  814.22   387.1  815.17   399.1  822.49
   403.1  823.31   436.2  825.89   459.1  826.18   471.1  835.26   488.3  844.91
     505  856.76   531.2  880.48   535.2   882.4   547.2  883.01   551.2  884.96
   556.8  890.11   567.3  901.75   583.3  917.02   607.4  930.01   613.4  932.19
#Mann= 6 ,-1,0
       0      .1       0   154.9    .045       0   182.8      .1       0
  276.25     .05       0  376.25     .06       0  471.35      .1       0
Bank Sta=154.9,182.8
XS Rating Curve= 0 ,0
Exp/Cntr(USF)=0,0
Exp/Cntr=0.3,0.1

Type RM Length L Ch R = 1 ,5030    ,503.1,504.7,508.4
XS GIS Cut Line= 6
1664391.12517595396182.372072779 1664378.9076807 396363.20963762
1664367.11177253396537.8116506121664361.68658654396612.615962945
1664345.25387662396699.244398617 1664318.1656762396792.140866362
#Sta/Elev= 30
       0  851.51    26.2  847.72    50.3  845.41    58.3  843.81    62.3  842.42
    66.3  839.33    70.3  834.78    74.3  829.38    78.3  821.43    82.4  815.66
    86.4  812.31    90.4  809.54      95  807.88    98.4  807.62  116.04807.8978
   128.8   811.1   142.5  811.59   435.2   811.8   524.9  812.95   533.3  813.83
   550.4  816.49   560.1   816.9   574.9  816.75   579.1  818.63   583.3  821.84
   585.9  823.12   591.6  824.86   595.8  826.67   604.1  833.68   616.2  845.78
#Mann= 6 ,-1,0
       0      .1       0      95    .045       0  116.04      .1       0
  191.25     .08       0  491.25     .06       0  589.42      .1       0
Bank Sta=95,116.04
XS Rating Curve= 0 ,0
Exp/Cntr(USF)=0,0
Exp/Cntr=0.3,0.1