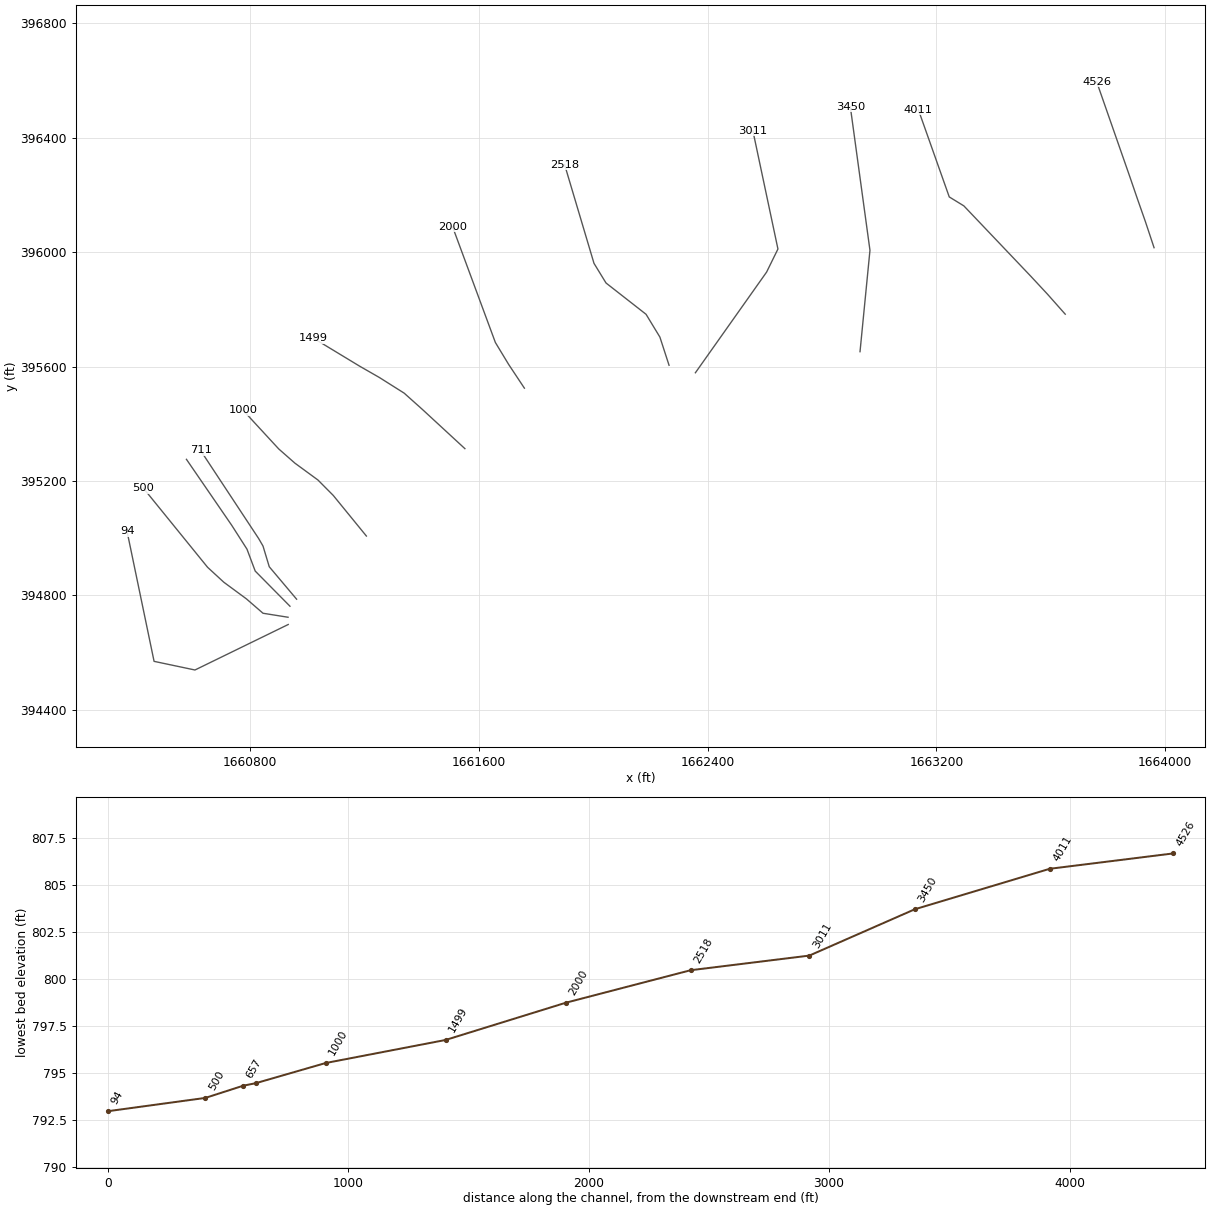
HEC-RAS study WILLEYFK.prj: WILLEYFK

--- WILLEYFK.g01 (geometry) --- (continued)

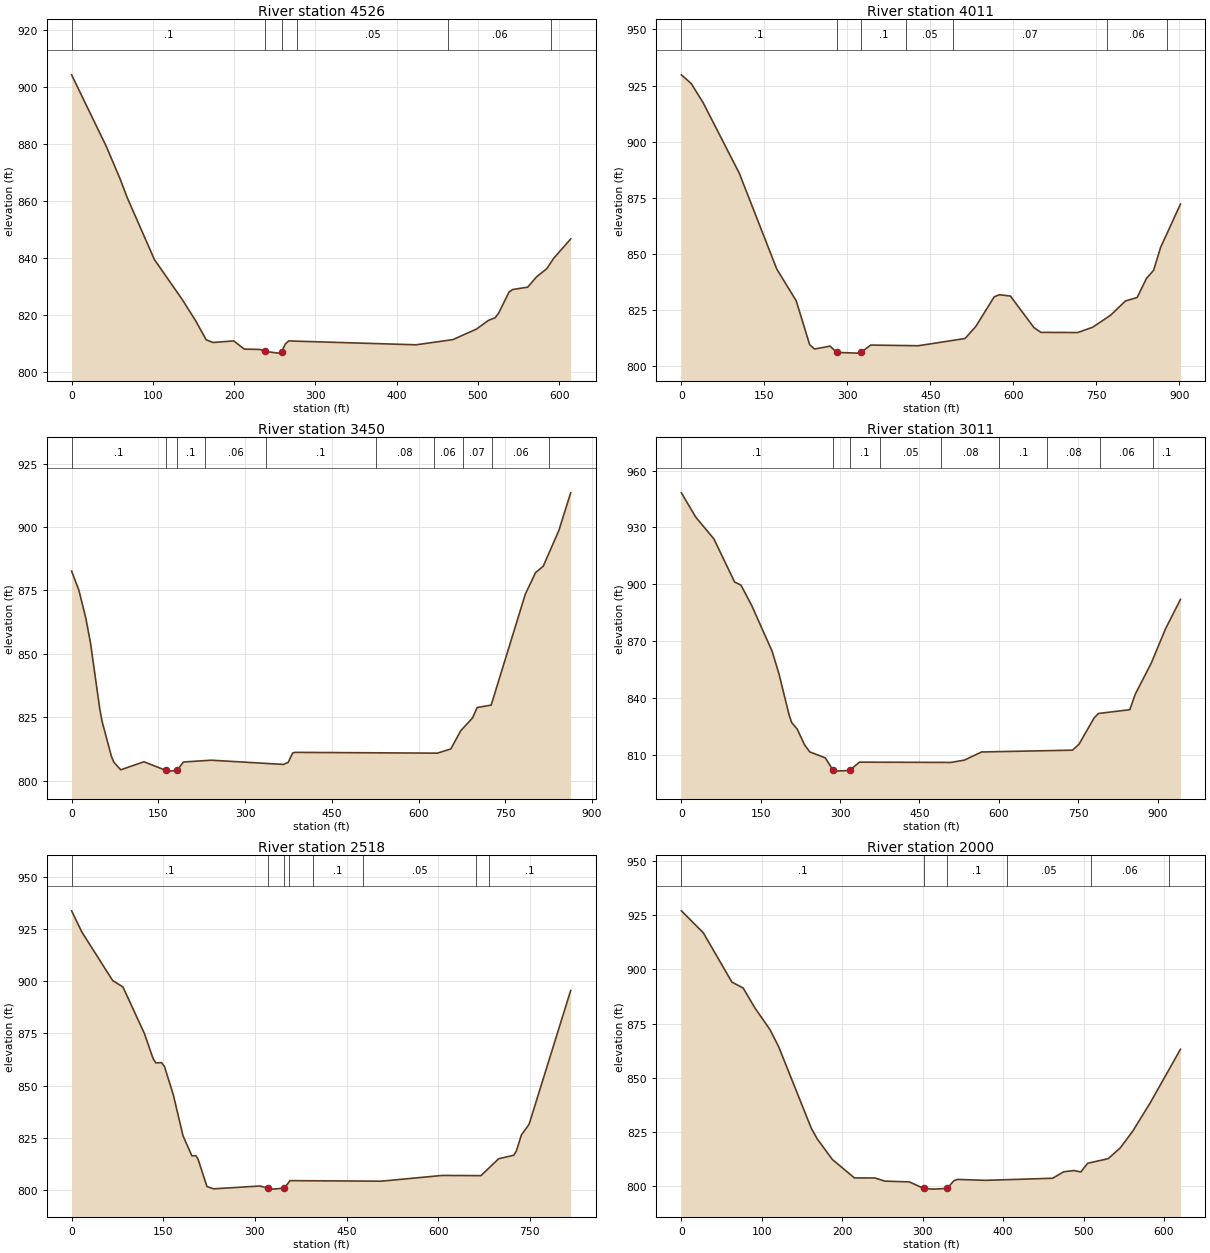
Type RM Length L Ch R = 1 ,4526    ,504.5,514.2,519.8
XS GIS Cut Line= 6
1663961.09432063396015.7259425481663931.02843588396106.247743126
 1663902.0399768396188.884060796 1663877.7526238396259.844548802
1663844.78287346396354.2531526341663760.30043088396596.176225211
#Sta/Elev= 30
       0  904.23      43  878.94    59.9  867.61    68.3  861.28     102  839.44
     136  825.56   152.8  817.97   165.6  811.38   174.1  810.42   199.5  810.99
   212.5  808.11   231.4  807.99  238.28807.2991   254.5   806.7   258.7  807.26
   262.9  809.88   267.2  810.97   423.9  809.62   469.2  811.43   498.4  815.14
   512.9  818.16   521.4  819.13   525.6  820.74   538.3  828.08   542.6  828.98
   561.3  829.82   572.2  833.43   584.9  836.32   593.4  839.97   614.2  846.71
#Mann= 6 ,-1,0
       0      .1       0  238.28    .045       0   258.7      .1       0
  277.96     .05       0  462.96     .06       0  590.46      .1       0
Bank Sta=238.28,258.7
XS Rating Curve= 0 ,0
Exp/Cntr(USF)=0,0
Exp/Cntr=0.3,0.1

Type RM Length L Ch R = 1 ,4011    ,573.9,561.5,547.6
XS GIS Cut Line= 6
1663650.45439109395783.2490859181663588.20189093395853.423158169
1663528.58980542395917.4824132621663295.94952267396161.991766751
 1663244.9051397  396193.28807051663136.86936821396498.370240813
#Sta/Elev= 30
       0  929.77    17.8  925.87    39.2   917.4   104.6  885.99   172.5  843.28
   207.6  829.16   231.9  809.65   240.7  807.71     269     809   280.7   806.2
     318  805.88  324.65806.2162   342.3  809.47   428.5  809.17   512.8  812.39
   532.2  817.71   565.5  830.93   574.9  831.88   594.9  831.29   637.3  817.28
     650  815.12   716.6  815.05   743.4  817.38   776.1  822.78   802.8  829.08
     824  830.65     841   839.2   853.7  842.73   866.4  852.94   902.3  872.23
#Mann= 7 ,-1,0
       0      .1       0   280.7    .045       0  324.65      .1       0
  406.31     .05       0  491.31     .07       0  768.69     .06       0
  878.69      .1       0
Bank Sta=280.7,324.65
XS Rating Curve= 0 ,0
Exp/Cntr(USF)=0,0
Exp/Cntr=0.3,0.1

Type RM Length L Ch R = 1 ,3450    ,449.5,438.5,431.3
XS GIS Cut Line= 6
1662932.82257823395652.043799856 1662941.9728224395745.346434765
1662950.51283156395832.4286096921662957.83302691395907.070520767
1662967.59252182 396006.593287611662898.90787797396508.805155949
#Sta/Elev= 30
       0  882.62    12.6  875.08    24.6  864.03    32.6  854.37    48.7  828.25
    52.7   823.3    68.8  809.59    72.8  807.33    84.9  804.23   125.1  807.41
   163.1803.9956   169.3  803.72  182.18803.9861   193.4  807.32   241.6  808.03
   366.3  806.36   374.4  807.16   382.4  810.88   385.9  811.12   632.7  810.81
   655.8  812.47   673.1   819.7   693.3  824.68   701.4  828.82   725.6  829.76
   784.7  873.56   802.3  881.99   815.7  884.58   842.7  898.66   863.1   913.5
#Mann= 10 ,-1,0
       0      .1       0   163.1    .045       0  182.18      .1       0
  231.25     .06       0  336.25      .1       0  526.25     .08       0
  626.25     .06       0  676.25     .07       0  726.25     .06       0
  826.25      .1       0
Bank Sta=163.1,182.18
XS Rating Curve= 0 ,0
Exp/Cntr(USF)=0,0
Exp/Cntr=0.3,0.1

Type RM Length L Ch R = 1 ,3011    ,477.5,493.5,523
XS GIS Cut Line= 6
1662357.16235825395578.4302698371662411.29873292395654.969814926
1662562.88241926 395869.279753761662606.19138776395930.511586666
1662645.81499617 396011.204338671662558.26757158396424.200006602
#Sta/Elev= 30
       0  948.24    27.1  935.41    61.4  923.92   100.6  901.12   112.7  899.47
   132.8  888.78   171.4  864.63   184.4  852.66   203.5     831   208.4  826.91
   218.9  823.45   232.9  815.07   242.7  811.39   272.1  808.24   286.7  801.64
   291.6  801.25  317.75 801.613   336.5  805.99   509.3  805.84   534.8  807.06
   567.4  811.37   739.2  812.32   751.5  815.44   780.1  829.34   788.3   831.7
   847.6   833.7   857.9   841.9   888.1  858.29     915  876.37   943.3  891.96
#Mann= 9 ,-1,0
       0      .1       0   286.7    .045       0  317.75      .1       0
  376.25     .05       0  491.25     .08       0  601.15      .1       0
  691.15     .08       0  791.15     .06       0  891.15      .1       0
Bank Sta=286.7,317.75
XS Rating Curve= 0 ,0
Exp/Cntr(USF)=0,0
Exp/Cntr=0.3,0.1

Type RM Length L Ch R = 1 ,2518    ,517.1,518,498.2
XS GIS Cut Line= 6
1662265.01293626395604.6487213371662233.02448317395703.145571589
1662184.63055108395782.8658845871662044.60819334395892.312516093
1662002.53084968395961.0610662551661899.77181827396306.276520856
#Sta/Elev= 30
       0  933.61    16.7  923.51    67.2  900.25      84  897.19   119.2   874.9
   133.3  862.97   137.9  860.87   147.3  860.99     152  859.11   166.4  845.66
   182.4  825.94   196.8  816.42   203.3  816.49   206.9  814.85   221.5  801.71
   232.7  800.62   308.3  801.96   321.2  800.91   329.2  800.47   348.1  800.94
   357.5  804.53   507.1  804.27   606.5  807.02     670  806.92     699     815
   723.9  816.69     728  818.72   736.3  826.43   748.8  831.47   816.9  895.49
#Mann= 8 ,-1,0
       0      .1       0   321.2    .045       0   348.1      .1       0
  355.64     .05       0  395.79      .1       0  476.39     .05       0
  662.42     .06       0  682.42      .1       0
Bank Sta=321.2,348.1
XS Rating Curve= 0 ,0
Exp/Cntr(USF)=0,0
Exp/Cntr=0.3,0.1

Type RM Length L Ch R = 1 ,2000    ,490.5,501.2,498
XS GIS Cut Line= 6
1661759.17536525395524.5839208361661704.14726008395607.514529258
1661657.67884909395684.2922628371661631.66184075 395754.63496992
 1661596.9722776395848.4254647491661508.08072309396088.763238668
#Sta/Elev= 30
       0  927.04    27.2  916.93    62.8  894.19    76.8  891.45    91.2  882.38
   110.1  872.29   120.7   864.6   161.5  826.81   169.1  821.79   187.7  812.41
   215.1  803.91   240.7  803.88   252.9  802.43   283.4  802.08  301.25799.0549
   313.2  798.74   330.3  799.03   338.8  802.61   343.1  803.22   378.3  802.79
   461.5  803.75   475.3  806.73   488.1   807.3   496.6  806.66   505.1  810.66
   530.7  812.79   545.6  817.73   561.2  825.48     583  838.58   620.5  863.22
#Mann= 6 ,-1,0
       0      .1       0  301.25    .045       0   330.3      .1       0
  404.27     .05       0  509.27     .06       0  606.77      .1       0
Bank Sta=301.25,330.3
XS Rating Curve= 0 ,0
Exp/Cntr(USF)=0,0
Exp/Cntr=0.3,0.1

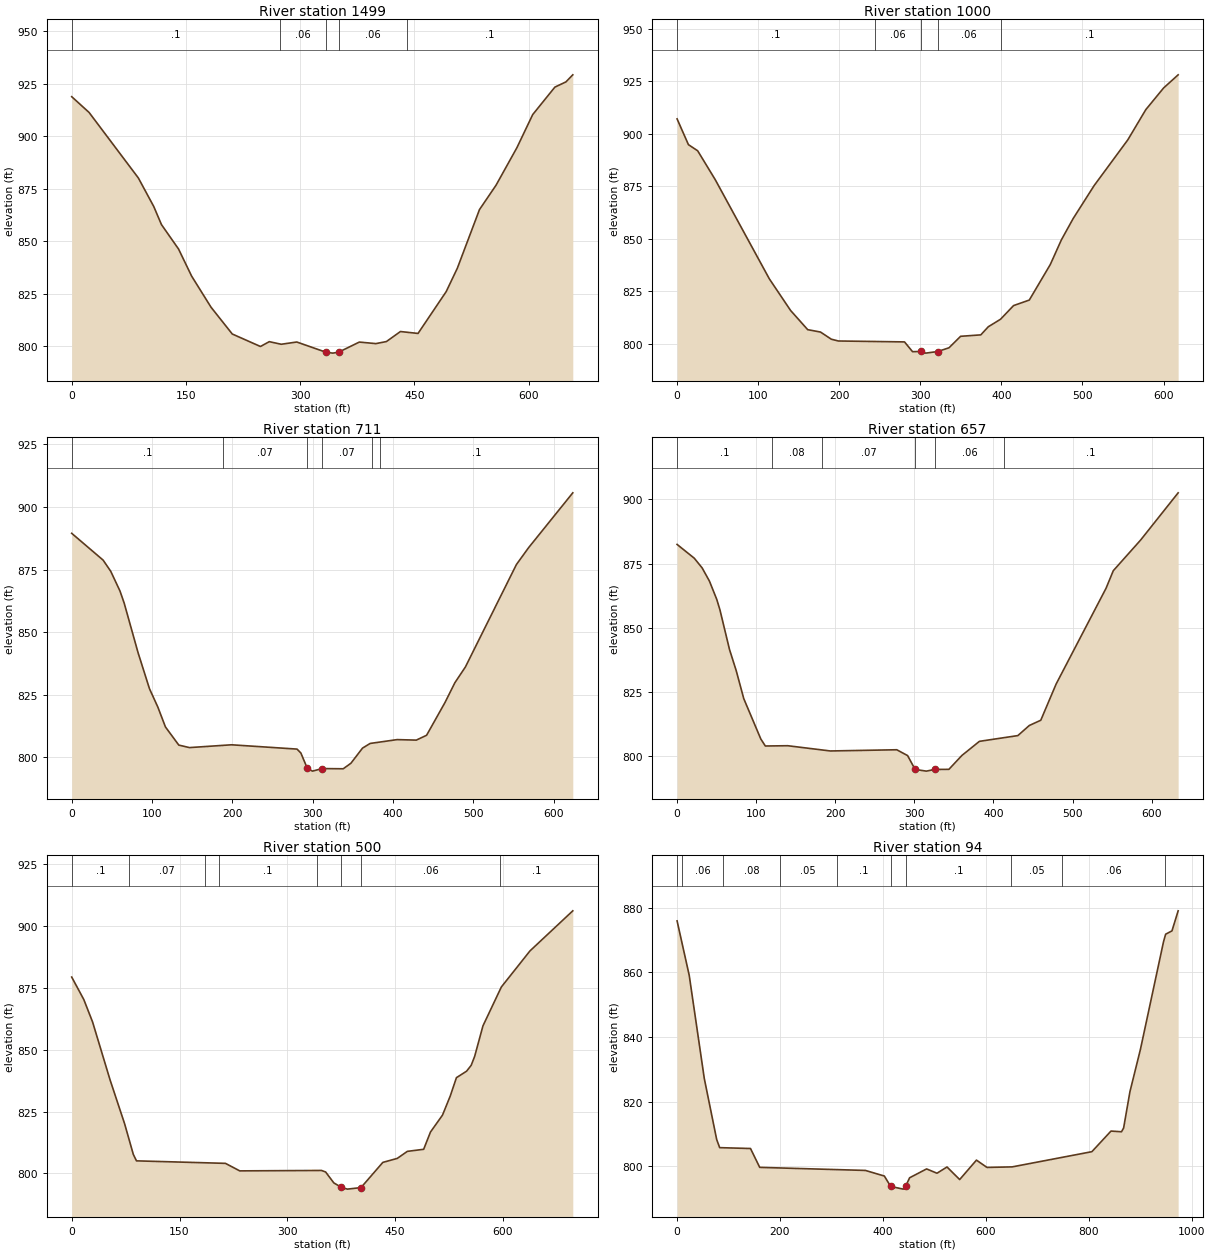
Type RM Length L Ch R = 1 ,1499    ,496.3,498.8,492.7
XS GIS Cut Line= 6
1661551.11639817395313.0518635961661401.57437442395451.010249093
1661338.68703301 395507.173850671661252.29481734395561.710815087
1661183.07349908395601.4039771711661022.14140625395698.904438332
#Sta/Elev= 30
       0  918.81    22.8  911.31    87.5  880.12   107.7  866.56   117.8  857.95
   140.3  846.29   157.4  833.44   182.9  818.61   210.8  805.85   247.8  799.91
   259.4  802.21   275.1  800.97   295.5  802.04   334.1  797.14   342.8  796.75
   350.3  797.17   377.6  802.01   399.4  801.28   413.2  802.26   431.6  807.03
   454.7  806.12   491.7  826.04   506.3  837.15   535.4  865.08   557.1  876.66
   584.5  894.52   605.3  910.31   634.4  923.37   648.9  925.86   657.9  929.22
#Mann= 5 ,-1,0
       0      .1       0  273.46     .06       0   334.1    .045       0
   350.3     .06       0  439.94      .1       0
Bank Sta=334.1,350.3
XS Rating Curve= 0 ,0
Exp/Cntr(USF)=0,0
Exp/Cntr=0.3,0.1

Type RM Length L Ch R = 1 ,1000    ,290.9,289,283.4
BEGIN DESCRIPTION:
Structure XS 4
END DESCRIPTION:
XS GIS Cut Line= 6
1661206.62857009395007.4238659291661090.56121692395149.707374007
1661037.28802951395203.3339071721660956.58412267395262.383985922
1660900.03272659395312.1053431781660775.72818518395446.889850512
#Sta/Elev= 30
       0  907.03      14  894.76    25.4  891.84    47.1  878.07   113.8  830.87
     140  815.83   161.1  806.69   176.9  805.55   190.2  802.15   198.9   801.3
   280.5  800.86   290.4  796.21   300.4   796.3   306.7  795.52  321.43796.2815
   335.4  798.07   349.7  803.53   374.6  804.21   383.8  808.06   398.9  811.64
     415  818.15   434.4  820.78   460.3  837.69     474  849.46   488.5  859.58
   514.3  875.24   555.9  897.04   578.1  911.43   600.1  921.76     618     928
#Mann= 5 ,-1,0
       0      .1       0  243.66     .06       0   300.4    .045       0
  321.43     .06       0  399.25      .1       0
Bank Sta=300.4,321.43
XS Rating Curve= 0 ,0
Exp/Cntr(USF)=0,0
Exp/Cntr=0.3,0.1

Type RM Length L Ch R = 1 ,711     ,54,53.8,53.8
BEGIN DESCRIPTION:
Structure XS 3
END DESCRIPTION:
XS GIS Cut Line= 5
1660962.62209208394786.6118848761660866.99033512394900.003825275
1660845.13164781394972.4107269751660830.10380029394998.367918151
1660626.54477476395307.121876346
#Sta/Elev= 30
       0  889.46    39.1  878.75    48.6  874.28    60.1   866.4    65.3  861.59
    82.6  841.77    96.8  827.38   107.2  820.06   116.7  812.09   133.3  804.85
   146.6  803.85     199  804.97   280.5  803.25   285.3  801.68  293.33795.5074
   299.7  794.45   311.8  795.47     338  795.39   347.6   797.6     362  803.64
   371.5  805.51   405.1  807.04     429  806.84   441.8  808.78   464.9  821.98
     477  829.77   490.1  836.06   553.6  876.98   568.8  883.73   623.8  905.64
#Mann= 6 ,-1,0
       0      .1       0  188.33     .07       0  293.33    .045       0
   311.8     .07       0  373.96     .06       0  383.96      .1       0
Bank Sta=293.33,311.8
XS Rating Curve= 0 ,0
Exp/Cntr(USF)=0,0
Exp/Cntr=0.3,0.1

Type RM Length L Ch R = 1 ,657     ,155,157.3,158.4
BEGIN DESCRIPTION:
Structure XS 2
END DESCRIPTION:
XS GIS Cut Line= 5
1660939.39723682394762.0208616571660817.80828868394884.975977752
1660789.11876159394961.4813833221660735.83821129395044.817628676
1660577.36272832395275.700013344
#Sta/Elev= 30
       0  882.48    21.7  877.12    31.7  873.33    40.9  868.22    50.2  861.07
    54.2  857.02    66.3   841.6    74.8  833.36    84.3  822.52   105.9  806.79
   111.6  804.08   139.9  804.19   193.8  802.15   277.8  802.62   291.5  800.35
     301  794.97     301  794.96   315.2  794.31  325.85794.9673   343.7     795
   360.1  800.39   382.3  805.89   430.9  808.13   445.4  812.06   459.9   814.1
   479.3  828.18   542.4  865.41   551.6  872.26   586.1  884.16   633.6  902.54
#Mann= 6 ,-1,0
       0      .1       0     120     .08       0  182.92     .07       0
     301    .045       0  325.85     .06       0  413.54      .1       0
Bank Sta=301,325.85
XS Rating Curve= 0 ,0
Exp/Cntr(USF)=0,0
Exp/Cntr=0.3,0.1

Type RM Length L Ch R = 1 ,500     ,392,406.1,411.9
BEGIN DESCRIPTION:
Structure XS 1
END DESCRIPTION:
XS GIS Cut Line= 6
1660932.74787498394723.4388406331660845.13164781394737.429838438
1660787.02114159394787.7779797611660708.03015783 394845.95699726
1660651.22056018394898.2626669261660426.78170459395174.910735667
#Sta/Elev= 30
       0  879.31    16.8  870.25      29   861.2    53.3  837.84    73.6  820.06
    85.7   807.7    90.1  805.08   213.9  804.07   233.8  801.03   347.6   801.2
   353.3  800.58   364.7  796.18     375  794.41   383.6  793.66   402.5  794.28
   432.9  804.46   452.9  806.06     467  808.91   489.7  809.75   499.2  816.73
   515.9  823.55   526.7  831.27   535.3  838.68   549.4  841.29   555.8  843.65
   560.7  847.32   572.2   859.6   597.8  875.31   637.6  889.87   697.2  906.07
#Mann= 8 ,-1,0
       0      .1       0      80     .07       0  185.61     .08       0
  205.61      .1       0  340.94     .06       0     375    .045       0
   402.5     .06       0  595.94      .1       0
Bank Sta=375,402.5
XS Rating Curve= 0 ,0
Exp/Cntr(USF)=0,0
Exp/Cntr=0.3,0.1

Type RM Length L Ch R = 1 ,94      ,,,
XS GIS Cut Line= 4
1660933.33483189394698.0849782791660607.15675985394539.022832036
1660464.20217272394569.2245053731660369.57026293395024.263050322
#Sta/Elev= 30
       0  875.92    23.6  859.07    52.9  827.15      77  808.27    82.8  805.78
   142.7  805.51   160.6  799.68     366  798.73   402.8     797   415.1  793.78
   439.6  792.95  444.01793.7844   451.9  796.46   484.9   799.2   505.1  797.87
   524.6   799.8   549.2  795.91   581.8  801.92   602.3  799.66   651.3  799.83
   806.1  804.53   843.3  810.91   863.7  810.69   867.8  811.86   880.1  823.09
   900.5  836.19   945.5  869.57   949.5   871.8   961.8  872.83   973.8  879.03
#Mann= 10 ,-1,0
       0      .1       0      10     .06       0      90     .08       0
     200     .05       0     310      .1       0   415.1    .045       0
  444.01      .1       0  649.01     .05       0  749.01     .06       0
  949.01      .1       0
Bank Sta=415.1,444.01
XS Rating Curve= 0 ,0
Exp/Cntr(USF)=0,0
Exp/Cntr=0.3,0.1
LCMann Table=0

Chan Stop Cuts=-1
Use User Specified Reach Order=0
Composite Channel Slope=5